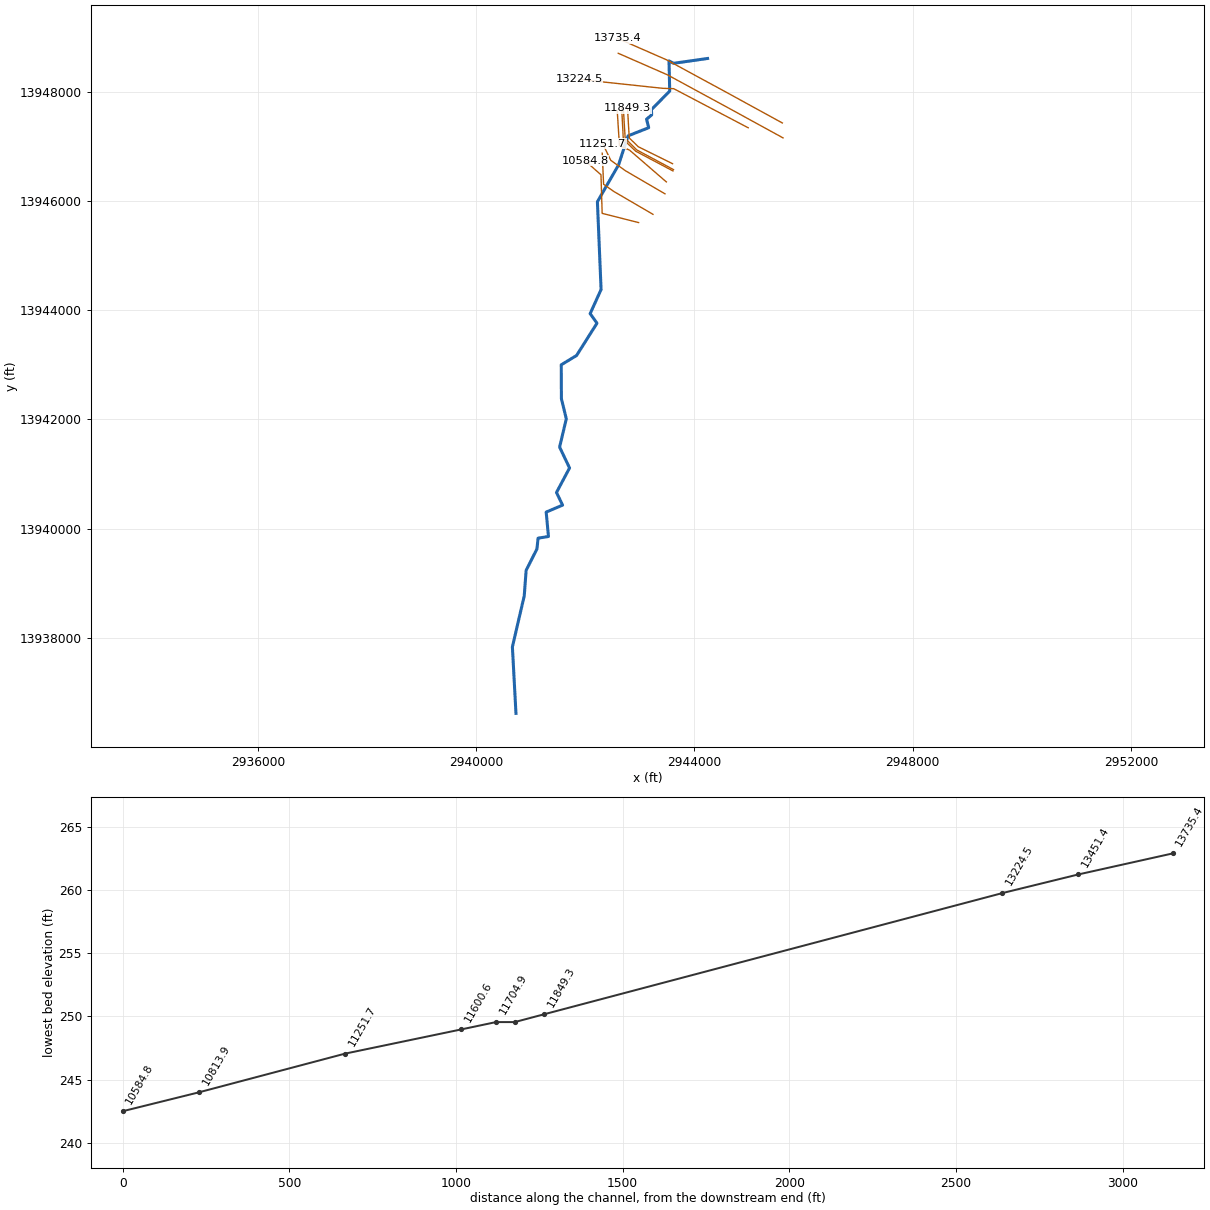
--- K166-01-00.prj (project) ---

Proj Title=K166-01-00
Current Plan=p02
Default Exp/Contr=.3,.1
English Units
Geom File=g01
Flow File=f01
Flow File=f04
Flow File=f02
Plan File=p01
Plan File=p04
Plan File=p02
Y Axis Title=Elevation
X Axis Title(PF)=Main Channel Distance
X Axis Title(XS)=Station
BEGIN DESCRIPTION:
Cypress Creek Watershed
Mound Creek Trib 8.18
HCFCD Unit K166-01-00
Flood Hazard Model
10, 2, 1, 0.2%
Filename K166-01-00
Prepared by:  Halff Associates Inc   DATE:  03-26-04
Reviewed by:  _____________________  DATE:  __________________
STATUS (Final)
END DESCRIPTION:
DSS Export Rating Curves= 0
DSS Export Rating Curve Sorted= 0
DSS Export Volume Flow Curves= 0
DXF OffsetX= 0
DXF OffsetY= 0
DXF ScaleX= 1
DXF ScaleY= 10

--- K166-01-00.p02 (plan) ---

Plan Title=Floodway
Version=Version 3.0.1  Mar 2001
Short Identifier=Floodway0607
Geom File=g01
Flow File=f02
Subcritical Flow
K Sum by GR= 0
Std Step Tol= 0.01
Critical Tol= 0.01
Num of Std Step Trials= 20
Max Error Tol= 0.3
Flow Tol Ratio= 0.001
Split Flow NTrial= 30
Split Flow Tol= 0.02
Split Flow Ratio= 0.02
Log Output Level= 0
Friction Slope Method= 1
Unsteady Friction Slope Method= 2
Parabolic Critical Depth
Global Vel Dist= 0 , 0 , 0
Global Log Level= 0
CheckData=True
Encroach Param=-1 ,0,0, 2
Encroach River=K166-01-00
Encroach Reach=Reach - 1
Encroach Node=13735.4
       1 3931.19  5034.7
Encroach Node=13593.4
       1 3931.19  5034.7
Encroach Node=13451.4
       1 3939.95  5034.7
Encroach Node=13224.5
       1    4840    5090
Encroach Node=11849.3
       1 4951.08  5042.6
Encroach Node=11760.9
       1 4951.08  5042.6
Encroach Node=11732.9
       1 4951.08  5042.6
Encroach Node=11704.9
       1 4951.08  5042.6
Encroach Node=11600.6
       1 4951.08  5042.6
Encroach Node=11251.7
       1  4962.2  5042.6
Encroach Node=10813.9
       1  4980.2  5024.3
Encroach Node=10584.8
       13359.8463621.978
Encroach Node=10535.8
       13359.8463621.978
Encroach Node=10486.7
       13359.8463621.978
Encroach Node=9975.2
       1 4886.225112.462
Encroach Node=9798.2
       1  4979.1 5167.06
Encroach Node=9761.2
       1  4979.1 5167.06
Encroach Node=9724.2
       1  4979.1 5167.06
Encroach Node=9628.10
       1  4979.1 5167.06
Encroach Node=9304.9
       1 4797.42 5155.86
Encroach Node=9204.9
       1 4797.42 5155.86
Encroach Node=9177.9
       1 4797.42 5155.86
Encroach Node=9150.9
       1 4797.42 5155.86
Encroach Node=8917.7
       1  4730.8 5187.95
Encroach Node=8889.0
       1  4730.8 5187.95
Encroach Node=8860.2
       1  4730.8 5217.95
Encroach Node=8796.1
       1 4704.95 5304.95
Encroach Node=8783.2
       1 4704.95 5304.95
Encroach Node=8770.2
       1 4704.95 5304.95
Encroach Node=8674.6
       1  4688.6  5288.6
Encroach Node=8628.7
       1  4688.6  5288.6
Encroach Node=8582.8
       1  4688.6  5288.6
Encroach Node=8480.3
       1  4699.8    5171
Encroach Node=8454.6
       1  4699.8    5171
Encroach Node=8428.9
       1  4729.8 5141.28
Encroach Node=8408.9
       1 4775.57    5125
Encroach Node=8376.9
       1 4775.57    5125
Encroach Node=8344.9
       1 4815.57 5110.69
Encroach Node=8127.6
       1 4881.23 5110.69
Encroach Node=7568.5
       1  4938.8 5071.65
Encroach Node=6555.9
       1 4829.75 5038.05
Encroach Node=5384.9
       1 4804.42  5024.3
Encroach Node=5284.9
       1 4804.42  5024.3
Encroach Node=5267.1
       1 4804.42  5024.3
Encroach Node=5249.3
       1 4804.42  5024.3
Encroach Node=5156.2
       1 4804.42  5024.3
Encroach Node=4283.4
       1 4954.74 5112.65
Encroach Node=2728.1
       1 4986.21 5243.62
Encroach Node=2459.5
       1  4964.3 5161.64
Encroach Node=2356.5
       1  4964.3 5161.64
Encroach Node=2334.8
       1  4964.3 5161.64
Encroach Node=2313.0
       1  4964.3 5161.64
Encroach Node=2277.0
       1  4956.3 5145.73
Encroach Node=2257.2
       1  4956.3 5128.73
Encroach Node=2237.4
       1  4956.3 5128.73
Encroach Node=2142.0
       1 4936.82    5100
Encroach Node=2126.7
       1 4936.82 5086.26
Encroach Node=2111.3
       1 4936.82 5086.26
Encroach Node=1952.4
       1    4840 5068.95
Encroach Node=1935.2
       1    4840 5068.95
Encroach Node=1918.0
       1    4840 5068.95
Encroach Node=1907.0
       1 4856.18 5079.87
Encroach Node=1885.4
       1 4856.18 5079.87
Encroach Node=1863.7
       1 4856.18 5079.87
Encroach Node=1768.8
       1 4856.18 5079.87
Encroach Node=877.1
       1 4819.23 5384.98
Encroach Node=769.1
       1 4819.23 5384.98
Encroach Node=743.1
       1 4819.23 5384.98
Encroach Node=717.1
       1 4819.23 5384.98
Encroach Reach=K166-01-00_0007
Encroach Node=13735.4
       1 3931.19  5034.7
Encroach Node=13593.4
       1 3931.19  5034.7
Encroach Node=13451.4
       1 3939.95  5034.7
Encroach Node=13224.5
       1    4840    5090
Encroach Node=11849.3
       1 4951.08  5042.6
Encroach Node=11760.9
       1 4951.08  5042.6
Encroach Node=11732.9
       1 4951.08  5042.6
Encroach Node=11704.9
       1 4951.08  5042.6
Encroach Node=11600.6
       1 4951.08  5042.6
Encroach Node=11251.7
       1  4962.2  5042.6
Encroach Node=10813.9
       1  4980.2  5024.3
Encroach Node=10584.8
       13359.8463621.978
Encroach Node=10535.8
       13359.8463621.978
Encroach Node=10486.7
       13359.8463621.978
Encroach Node=9975.2
       1 4886.225112.462
Encroach Node=9798.2
       1  4979.1 5167.06
Encroach Node=9761.2
       1  4979.1 5167.06
Encroach Node=9724.2
       1  4979.1 5167.06
Encroach Node=9628.10
       1  4979.1 5167.06
Encroach Node=9304.9
       1 4797.42 5155.86
Encroach Node=9204.9
       1 4797.42 5155.86
Encroach Node=9177.9
       1 4797.42 5155.86
Encroach Node=9150.9
       1 4797.42 5155.86
Encroach Node=8917.7
       1  4730.8 5187.95
Encroach Node=8889.0
       1  4730.8 5187.95
Encroach Node=8860.2
       1  4730.8 5217.95
Encroach Node=8796.1
       1 4704.95 5304.95
Encroach Node=8783.2
       1 4704.95 5304.95
Encroach Node=8770.2
       1 4704.95 5304.95
Encroach Node=8674.6
       1  4688.6  5288.6
Encroach Node=8628.7
       1  4688.6  5288.6
Encroach Node=8582.8
       1  4688.6  5288.6
Encroach Node=8480.3
       1  4699.8    5171
Encroach Node=8454.6
       1  4699.8    5171
Encroach Node=8428.9
       1  4729.8 5141.28
Encroach Node=8408.9
       1 4775.57    5125
Encroach Node=8376.9
       1 4775.57    5125
Encroach Node=8344.9
       1 4815.57 5110.69
Encroach Node=8127.6
       1 4881.23 5110.69
Encroach Node=7568.5
       1  4938.8 5071.65
Encroach Node=6555.9
       1 4829.75 5038.05
Encroach Node=5384.9
       1 4804.42  5024.3
Encroach Node=5284.9
       1 4804.42  5024.3
Encroach Node=5267.1
       1 4804.42  5024.3
Encroach Node=5249.3
       1 4804.42  5024.3
Encroach Node=5156.2
       1 4804.42  5024.3
Encroach Node=4283.4
       1 4954.74 5112.65
Encroach Node=2728.1
       1 4986.21 5243.62
Encroach Node=2459.5
       1  4964.3 5161.64
Encroach Node=2356.5
       1  4964.3 5161.64
Encroach Node=2334.8
       1  4964.3 5161.64
Encroach Node=2313.0
       1  4964.3 5161.64
Encroach Node=2277.0
       1  4956.3 5145.73
Encroach Node=2257.2
       1  4956.3 5128.73
Encroach Node=2237.4
       1  4956.3 5128.73
Encroach Node=2142.0
       1 4936.82    5100
Encroach Node=2126.7
       1 4936.82 5086.26
Encroach Node=2111.3
       1 4936.82 5086.26
Encroach Node=1952.4
       1    4840 5068.95
Encroach Node=1935.2
       1    4840 5068.95
Encroach Node=1918.0
       1    4840 5068.95
Encroach Node=1907.0
       1 4856.18 5079.87
Encroach Node=1885.4
       1 4856.18 5079.87
Encroach Node=1863.7
       1 4856.18 5079.87
Encroach Node=1768.8
       1 4856.18 5079.87
Encroach Node=877.1
       1 4819.23 5384.98
Encroach Node=769.1
       1 4819.23 5384.98
Encroach Node=743.1
       1 4819.23 5384.98
Encroach Node=717.1
       1 4819.23 5384.98
Computation Interval=1HOUR
Output Interval=1HOUR
Run HTab= 0
Run UNet= 0
Run PostProcess= 0
UNET Theta= 1
UNET ZTol= 0.02
UNET ZSATol= 0.1
UNET MxIter= 20
UNET MaxInSteps= 20
UNET DtIC= 0
UNET DtMin= 0
UNET MaxCRTS= 20
UNET WFStab= 2
UNET SFStab= 1
UNET WFX= 1
UNET SFX= 1
UNET Convert EG Bridges=-1
UNET Use Existing IB Tables=-1
Instantaneous Interval=1HOUR
Write IC File= 0
Write Velocity= 0
Write Detailed= 0

--- K166-01-00.p01 (plan) ---

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Plan Title=FEMA Effective June 2007
Short Identifier=FEMAeff0607
Geom File=g01
Flow File=f01
Encroach Param=-1 ,0,0, 0
IC Time=0

--- K166-01-00.p04 (plan) ---

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Plan Title=Storage Routing
Short Identifier=Store_Rout
Geom File=g01
Flow File=f04
Encroach Param=-1 ,0,0, 0

--- K166-01-00.f02 (steady flow) ---

Flow Title=Floodway
Version=Version 3.0.1  Mar 2001
Number of Profiles= 2
Profile Names=1PCT_100yr, 1PCTFloodway_100yrFW
River Rch & RM=K166-01-00,K166-01-00_0007,13735.4
    1610    1610
River Rch & RM=K166-01-00,K166-01-00_0007,11760.9
    1690    1690
River Rch & RM=K166-01-00,K166-01-00_0007,10584.8
    1730    1730
River Rch & RM=K166-01-00,K166-01-00_0007,9798.2
    1800    1800
River Rch & RM=K166-01-00,K166-01-00_0007,8674.6
    1850    1850
River Rch & RM=K166-01-00,K166-01-00_0007,7568.5
    1950    1950
River Rch & RM=K166-01-00,K166-01-00_0007,5284.9
    2000    2000
River Rch & RM=K166-01-00,K166-01-00_0007,4283.4
    2400    2400
River Rch & RM=K166-01-00,K166-01-00_0007,2728.1
    2510    2510
River Rch & RM=K166-01-00,K166-01-00_0007,2356.5
    2630    2630
River Rch & RM=K166-01-00,K166-01-00_0007,1952.4
    2670    2670
River Rch & RM=K166-01-00,K166-01-00_0007,1907.0
    3052    3052
Boundary for River Rch & Prof#=K166-01-00,K166-01-00_0007, 1
Up Type= 0
Dn Type= 3
Dn Slope=.0038
Boundary for River Rch & Prof#=K166-01-00,K166-01-00_0007, 2
Up Type= 0
Dn Type= 1
Dn Known WS=221.66
DSS Import GetInterval= 0
DSS Import GetPeak= 0
DSS Import FillOption= 0

--- K166-01-00.f01 (steady flow) ---

Flow Title=FEMA Effective June 2007
Version=Version 3.0.1  Mar 2001
Number of Profiles= 4
Profile Names=10PCT_10yr, 2PCT_50yr, 1PCT_100yr, 0.2PCT_500yr
River Rch & RM=K166-01-00,K166-01-00_0007,13735.4
     810    1380    1610    2250
River Rch & RM=K166-01-00,K166-01-00_0007,11760.9
     860    1460    1690    2420
River Rch & RM=K166-01-00,K166-01-00_0007,10584.8
     900    1510    1730    2530
River Rch & RM=K166-01-00,K166-01-00_0007,9798.2
     950    1600    1800    2700
River Rch & RM=K166-01-00,K166-01-00_0007,8674.6
     990    1620    1850    2750
River Rch & RM=K166-01-00,K166-01-00_0007,7568.5
    1070    1680    1950    2850
River Rch & RM=K166-01-00,K166-01-00_0007,5284.9
    1100    1700    2000    2900
River Rch & RM=K166-01-00,K166-01-00_0007,4283.4
    1320    2040    2400    3490
River Rch & RM=K166-01-00,K166-01-00_0007,2728.1
    1370    2140    2510    3650
River Rch & RM=K166-01-00,K166-01-00_0007,2356.5
    1440    2240    2630    3820
River Rch & RM=K166-01-00,K166-01-00_0007,1952.4
    1450    2270    2670    3880
River Rch & RM=K166-01-00,K166-01-00_0007,1907.0
    1657    2593    3052    4438
Boundary for River Rch & Prof#=K166-01-00,K166-01-00_0007, 1
Up Type= 0
Dn Type= 3
Dn Slope=.0038
Boundary for River Rch & Prof#=K166-01-00,K166-01-00_0007, 2
Up Type= 0
Dn Type= 3
Dn Slope=.0038
Boundary for River Rch & Prof#=K166-01-00,K166-01-00_0007, 3
Up Type= 0
Dn Type= 3
Dn Slope=.0038
Boundary for River Rch & Prof#=K166-01-00,K166-01-00_0007, 4
Up Type= 0
Dn Type= 3
Dn Slope=.0038
DSS Import GetInterval= 0
DSS Import GetPeak= 0
DSS Import FillOption= 0

--- K166-01-00.f04 (steady flow) ---

Flow Title=Storage Routing
Version=Version 3.0.1  Mar 2001
Number of Profiles= 8
Profile Names=0.25*10% flood, 0.50*10%flood, 10% flood, 4% flood, 2% flood, 1% flood, 0.2%flood, 1.25*0.2% flood
River Rch & RM=K166-01-00,K166-01-00_0007,13735.4
      75     150     300     430     540     670     810    1013
River Rch & RM=K166-01-00,K166-01-00_0007,9798.2
      85     170     340     480     600     740     900    1125
River Rch & RM=K166-01-00,K166-01-00_0007,8674.6
     110     220     440     620     770     970    1190    1488
Boundary for River Rch & Prof#=K166-01-00,K166-01-00_0007, 1
Up Type= 0
Dn Type= 3
Dn Slope=.0038
Boundary for River Rch & Prof#=K166-01-00,K166-01-00_0007, 2
Up Type= 0
Dn Type= 3
Dn Slope=.0038
Boundary for River Rch & Prof#=K166-01-00,K166-01-00_0007, 3
Up Type= 0
Dn Type= 3
Dn Slope=.0038
Boundary for River Rch & Prof#=K166-01-00,K166-01-00_0007, 4
Up Type= 0
Dn Type= 3
Dn Slope=.0038
Boundary for River Rch & Prof#=K166-01-00,K166-01-00_0007, 5
Up Type= 0
Dn Type= 3
Dn Slope=.0038
Boundary for River Rch & Prof#=K166-01-00,K166-01-00_0007, 6
Up Type= 0
Dn Type= 3
Dn Slope=.0038
Boundary for River Rch & Prof#=K166-01-00,K166-01-00_0007, 7
Up Type= 0
Dn Type= 3
Dn Slope=.0038
Boundary for River Rch & Prof#=K166-01-00,K166-01-00_0007, 8
Up Type= 0
Dn Type= 3
Dn Slope=.0038
DSS Import GetInterval= 0
DSS Import GetPeak= 0
DSS Import FillOption= 0

--- K166-01-00.g01 (geometry) ---

Geom Title=K166-01-00 June 2007
Version=Version 3.0.1  Mar 2001

River Reach=K166-01-00      ,K166-01-00_0007
Reach XY= 30
      2944240.29      13948605.5      2943617.01     13948517.03
      2943533.86     13948561.23      2943546.55       13948008.
      2943211.41     13947669.54      2943215.94     13947572.41
      2943122.33      13947493.9      2943161.59     13947338.39
      2942782.97     13947188.64      2942609.67     13946658.43
      2942221.49     13945982.32      2942288.88     13944376.29
      2942088.68     13943934.93      2942213.84       13943760.
      2941839.86     13943169.05      2941558.89     13942998.28
       2941561.6      13942379.2      2941651.34       13942010.
      2941528.94     13941491.77      2941711.24     13941110.26
      2941471.65     13940661.04      2941583.48     13940430.08
      2941282.85     13940302.96      2941324.52     13939856.35
      2941134.41      13939825.1      2941113.58     13939628.49
       2940915.3     13939236.17      2940881.06     13938770.79
      2940663.68     13937834.69      2940729.07      13936618.5

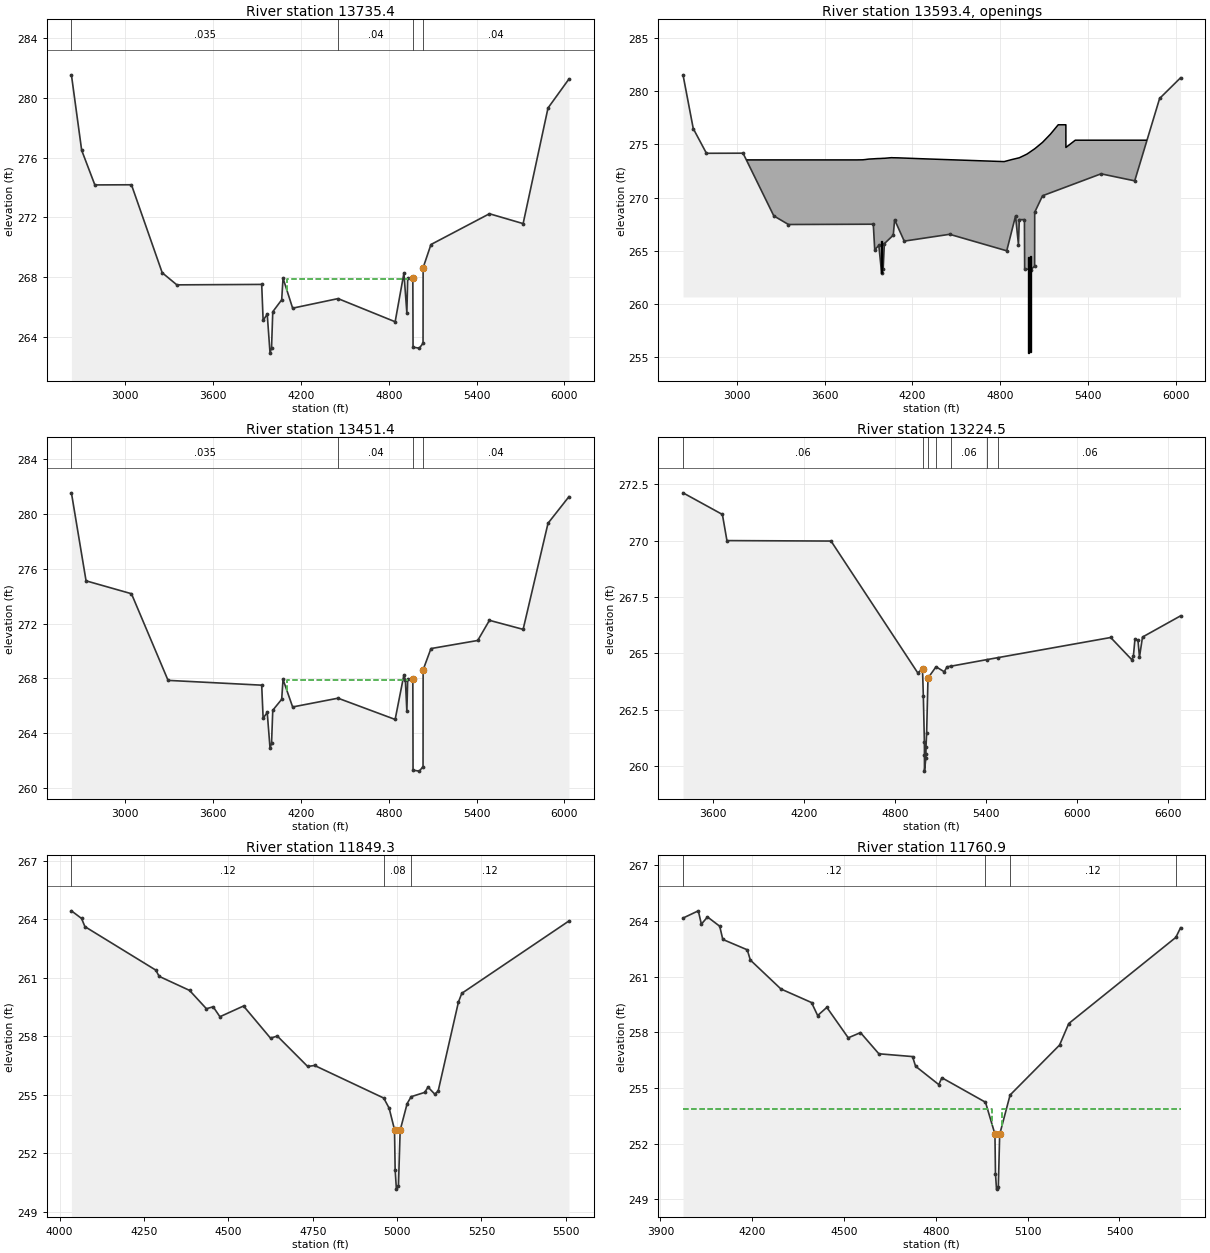
Type RM Length L Ch R = 1 ,13735.4 ,299.3,284,267.8
BEGIN DESCRIPTION:
K166-01-00-s20-US290-XS4
END DESCRIPTION:
XS GIS Cut Line= 4
      2945610.33     13947425.08      2944618.62     13947967.97
      2943490.06     13948580.27       2942589.5      13948974.1
#Sta/Elev= 30
    2633  281.54    2703  276.49    2793  274.17    3043  274.18    3253  268.29
    3353  267.48  3932.4  267.51  3942.1   265.1  3970.1  265.52  3989.3  262.91
  3999.6  263.27  4007.9  265.68  4068.9  266.48    4078  267.93  4143.6  265.92
  4453.6  266.56  4843.6  265.01  4903.6  268.27  4923.6   265.6  4929.3  267.94
  4964.4  267.94  4965.9  263.31  5008.6  263.24  5034.1  263.57  5034.7  268.63
  5088.1  270.18  5487.5  272.24  5717.5  271.58  5887.5  279.32  6030.4  281.26
#Mann= 4 ,-1 , 0
    2633    .035       0  4453.6     .04       0  4964.4     .02       0
  5034.7     .04       0
#XS Ineff= 1 ,-1
    4106    4931   267.9
Permanent Ineff=
       F
Bank Sta=4964.4,5034.7
XS Rating Curve= 0
Exp/Cntr=.5,.3

Type RM Length L Ch R = 4 ,13593.4 ,,,
BEGIN DESCRIPTION:
US290; Relief structure 11/15/2 VRR
Based off photo (see rail and ground-width should be larger than height
Culvert size appears to be wrong. 11/15/2 VRR
Structure ID: K166-01-00-S20
END DESCRIPTION:
Bridge Culvert--1,0,-1,-1, 0
Deck Dist Width WeirC Skew NumUp NumDn MinLoCord MaxHiCord MaxSubmerge Is_Ogee
10,272,2.6,0, 52, 52, , , .95, 0, ,,,
  3073.1 3753.49  3753.6 3753.71  3753.8  3765.7  3807.8  3821.7  3860.6  3875.4
  3904.2  3932.4  3942.1  3955.2  3970.1  3976.8  3988.9  3989.1  3989.3  3989.6
  3999.6  4006.4  4007.9  4048.5  4058.2  4068.9    4078  4106.2  4280.2  4468.9
  4825.9  4877.8  4929.3  4964.4  4965.9  4982.1  4990.6  4998.4  5001.2  5008.6
  5034.1  5034.7    5036  5088.1  5142.2  5195.1 5247.29  5247.4  5247.5 5247.61
  5311.6  5795.2
  273.55  273.55  273.55  273.55  273.55  273.55  273.55  273.55  273.56  273.58
  273.63  273.65  273.66  273.67  273.68  273.68  273.69  273.69  273.69  273.69
   273.7   273.7   273.7  273.75  273.76  273.75  273.75  273.74  273.65  273.56
  273.39  273.58  273.75  273.98  273.99   274.1  274.18  274.25  274.28  274.35
  274.59   274.6  274.61   275.2  275.97  276.85  276.85  276.85  276.85  274.72
   275.4   275.4
                                                                                
                                                                                
                                                                                
                                                                                
                                                                                
                
  3073.1 3753.49  3753.6 3753.71  3753.8  3765.7  3807.8  3821.7  3860.6  3875.4
  3904.2  3932.4  3942.1  3955.2  3970.1  3976.8  3988.9  3989.1  3989.3  3989.6
  3999.6  4006.4  4007.9  4048.5  4058.2  4068.9    4078  4106.2  4280.2  4468.9
  4825.9  4877.8  4929.3  4964.4  4965.9  4982.1  4990.6  4998.4  5001.2  5008.6
  5034.1  5034.7    5036  5088.1  5142.2  5195.1 5247.29  5247.4  5247.5 5247.61
  5311.6  5795.2
  273.55  273.55  273.55  273.55  273.55  273.55  273.55  273.55  273.56  273.58
  273.63  273.65  273.66  273.67  273.68  273.68  273.69  273.69  273.69  273.69
   273.7   273.7   273.7  273.75  273.76  273.75  273.75  273.74  273.65  273.56
  273.39  273.58  273.75  273.98  273.99   274.1  274.18  274.25  274.28  274.35
  274.59   274.6  274.61   275.2  275.97  276.85  276.85  276.85  276.85  274.72
   275.4   275.4
                                                                                
                                                                                
                                                                                
                                                                                
                                                                                
                
BR Coef= 1 , 0 , 0 ,1.25, 0 ,,,.8,0,2,0,
WSPro=,,,, 1 ,,,, 0 ,,,, 0 ,,,,-1 ,-1 ,-1 , 0 , 0 , 0 , 0 , 0
BR Coef= 1 , 0 , 0 ,1.25, 0 ,,,.8,0,2,0,
WSPro=,,,, 1 ,,,, 0 ,,,, 0 ,,,,-1 ,-1 ,-1 , 0 , 0 , 0 , 0 , 0
Culvert=2,3,4,272,.013,.4,1,8,1,262.96,3989.6,261.56,3989.6,Culvert #1  , 0 ,10
Culvert Bottom n=.013
Culvert=2,9,7,272,.013,.7,1,8,3,255.4,4994.5,254.5,4994.5,Culvert #2  , 0 ,10
Culvert Bottom n=.013
Culvert=2,9,7,272,.013,.7,1,8,3,255.49,5005.2,254.53,5005.2,Culvert #3  , 0 ,10
Culvert Bottom n=.013
BC Mult= 2 ,2633,4947,2633,4947
BC Mult= 2 ,4080,6030.4,4080,6030.4
BR D #Sta/Elev= 126
    2633  281.54    2703  276.49    2733  275.12    2793  274.17    2993  274.32
    3043  274.18    3093  272.78    3143  271.38    3153  270.56    3193  269.86
    3203  269.95    3233  268.81    3243  268.85    3253  268.29    3263  268.22
    3273  268.74    3293  267.86    3313  268.38    3333  267.87    3343  267.98
    3353  267.48    3373  268.48    3383  267.64    3403  267.27    3413  267.47
    3443  267.09    3463  267.77    3483  267.17    3493  267.58    3513     267
    3533  267.56    3543  267.22    3563   267.7    3653  267.42    3663     267
    3673  267.09    3683  267.65    3703  267.14    3713  267.74    3733  266.96
    3743  267.35  3765.7   267.5  3807.8  267.17  3821.7  267.06  3860.6   267.1
  3875.4  267.11  3904.2  267.31  3932.4  267.51  3942.1   265.1  3955.2   265.3
  3970.1  265.52  3976.8  263.75  3988.9  262.96  3989.1  262.92  3989.3  262.91
  3989.6  263.04  3999.6  263.27  4006.4  265.24  4007.9  265.68  4048.5  266.39
  4058.2  266.43  4068.9  266.48    4078  267.93  4106.2  267.93  4113.6  267.43
  4133.6  266.71  4143.6  265.92  4163.6  266.47  4173.6   265.9  4213.6  266.52
  4253.6  265.99  4273.6  265.98  4283.6  266.44  4303.6  265.98  4313.6  266.53
  4333.6  265.96  4353.6  266.56  4363.6  265.83  4383.6  266.47  4403.6  265.89
  4423.6  266.35  4433.6  266.03  4453.6  266.56  4493.6  266.34  4503.6  266.55
  4523.6  265.96  4543.6  266.45  4553.6  266.18  4563.6  266.52  4583.6   266.1
  4603.6  266.42  4683.6  265.61  4703.6  265.66  4713.6  265.23  4743.6  265.09
  4763.6   265.7  4783.6  265.25  4843.6  265.01  4863.6  265.64  4883.6  267.41
  4903.6  268.27  4913.6  267.86  4923.6   265.6  4929.3  267.94  4964.4  267.94
  4965.9  261.31  4982.1  261.28  4990.6  261.27  4998.4  261.59  5001.2  261.37
  5008.6  261.24  5034.1  261.57  5034.7  268.63    5036  268.67  5088.1  270.18
  5377.5   271.2  5407.5  270.77  5487.5  272.24  5717.5  271.58  5737.5  272.38
  5747.5  273.63  5757.5  273.23  5887.5  279.32  5987.5  281.04  6027.5  281.19
  6030.4  281.26
BR D #Mann= 4
    2633    .035  4453.6     .04  4964.4     .02  5034.7     .04
BC Design=,, 0 ,, 0 ,,,,,,
BC HTab HWMax=281.54

Type RM Length L Ch R = 1 ,13451.4 ,210.1,226.9,250.7
BEGIN DESCRIPTION:
K166-01-00-s20-US290-XS3
END DESCRIPTION:
XS GIS Cut Line= 4
       2945623.6     13947151.66       2944631.9     13947694.55
      2943503.54     13948306.74      2942603.17     13948700.48
#Sta/Elev= 30
    2633  281.54    2733  275.12    3043  274.18    3293  267.86  3932.4  267.51
  3942.1   265.1  3970.1  265.52  3989.3  262.91  3999.6  263.27  4007.9  265.68
  4068.9  266.48    4078  267.93  4143.6  265.92  4453.6  266.56  4843.6  265.01
  4903.6  268.27  4913.6  267.86  4923.6   265.6  4929.3  267.94  4964.4  267.94
  4965.9  261.31  5008.6  261.24  5034.1  261.57  5034.7  268.63  5088.1  270.18
  5407.5  270.77  5487.5  272.24  5717.5  271.58  5887.5  279.32  6030.4  281.26
#Mann= 4 ,-1 , 0
    2633    .035       0  4453.6     .04       0  4964.4     .02       0
  5034.7     .04       0
#XS Ineff= 1 ,-1
    4106    4931   267.9
Permanent Ineff=
       F
Bank Sta=4964.4,5034.7
XS Rating Curve= 0
Exp/Cntr=.5,.3

Type RM Length L Ch R = 1 ,13224.5 ,1267.4,1375.2,1221.3
BEGIN DESCRIPTION:
K166-01-00-X45-US290-XS1
Brushes accross some forest area, so will see 0.1 n-values VRR
Lowered channel roughness value to 0.045 due to crossing profile. - JJA 3/16/03
END DESCRIPTION:
XS GIS Cut Line= 4
      2944984.57     13947337.02      2943619.43     13948053.09
      2943417.62     13948059.27      2941885.27     13948222.54
#Sta/Elev= 29
  3401.2  272.12  3661.2  271.16  3691.2     270  4378.4  269.98    4951  264.13
  4982.3  264.31  4987.8   263.1  4994.7  261.05  4995.1   260.5  4995.2  259.77
  5004.8  260.37  5004.9  260.54  5005.2  260.83  5009.6  261.48  5018.5   263.9
  5071.6   264.4  5125.8  264.18  5144.6   264.4  5172.7  264.43  5408.5  264.72
  5483.2  264.81  6224.6   265.7  6364.6  264.71  6374.6  264.88  6384.6  265.62
  6404.6  265.58  6414.6  264.83  6434.6  265.72  6685.7  266.66
#Mann= 7 ,-1 , 0
  3401.2     .06       0  4982.3      .1       0  5018.5     .06       0
  5071.6      .1       0  5172.7     .06       0  5408.5      .1       0
  5483.2     .06       0
#Block Obstruct= 2 , 0
                         6228.19          265.72
Bank Sta=4982.3,5018.5
XS Rating Curve= 0
Exp/Cntr=.3,.1

Type RM Length L Ch R = 1 ,11849.3 ,64.2,88.4,128.6
BEGIN DESCRIPTION:
K166-01-00-S18_IRONWOOD-XS4
LIDAR overbanks, interpolated channel
END DESCRIPTION:
XS GIS Cut Line= 5
      2943598.67     13946679.55      2942970.76      13946990.3
      2942807.27     13947148.62      2942800.27     13947226.82
      2942773.57     13947693.59
#Sta/Elev= 30
  4035.1  264.44  4065.1  264.05  4075.1  263.63  4285.1   261.4  4295.1  261.08
  4385.1  260.36  4435.1  259.42  4455.1  259.52  4475.1  259.01  4545.1  259.56
  4625.1  257.91  4645.1  258.02  4735.1  256.46  4755.7  256.51 4960.52  254.84
 4976.54  254.32 4992.45  253.22  4994.3  251.17 4998.02  250.17 5004.02  250.31
  5009.2  253.19 5029.95  254.56  5041.8  254.91  5081.8  255.13  5091.8   255.4
  5111.8  255.04  5121.8   255.2  5181.8  259.76  5191.8  260.21  5509.3  263.92
#Mann= 3 ,-1 , 0
  4035.1     .12       0 4960.52     .08       0  5041.8     .12       0
Bank Sta=4992.45,5009.2
XS Rating Curve= 0
Exp/Cntr=.5,.3

Type RM Length L Ch R = 1 ,11760.9 ,39,56,40.2
BEGIN DESCRIPTION:
K166-01-00-S18_IRONWOOD-XS3
Moved channel banks back to surveyed channel banks by JJA on 3/14/03.
END DESCRIPTION:
XS GIS Cut Line= 5
      2943616.42      13946571.4      2942941.15      13946932.8
      2942745.72      13947128.3      2942728.94      13947162.7
      2942696.28       13947707.
#Sta/Elev= 30
  3973.7  264.15  4023.7  264.54  4033.7  263.82  4053.7  264.21  4093.7  263.71
  4103.7     263  4183.7  262.44  4193.7  261.89  4293.7  260.33  4393.7   259.6
  4413.7   258.9  4443.7  259.34  4513.7   257.7  4553.7  257.98  4613.7  256.84
  4723.7  256.69  4733.7  256.17  4809.6  255.18  4819.6  255.55  4962.2  254.23
  4993.1  252.51  4994.8  250.39  4998.2  249.55  5004.1  249.67  5008.6   252.5
  5042.6  254.62  5204.3  257.31  5234.3  258.47  5584.3  263.11  5599.6  263.63
#Mann= 4 ,-1 , 0
  3973.7     .12       0  4962.2     .08       0  5042.6     .12       0
  5584.3     .99       0
#XS Ineff= 2 , 0
       0  4984.5  253.85  5015.5       0  253.85
Permanent Ineff=
       F       F
Bank Sta=4993.1,5008.6
XS Rating Curve= 0
Exp/Cntr=.5,.3

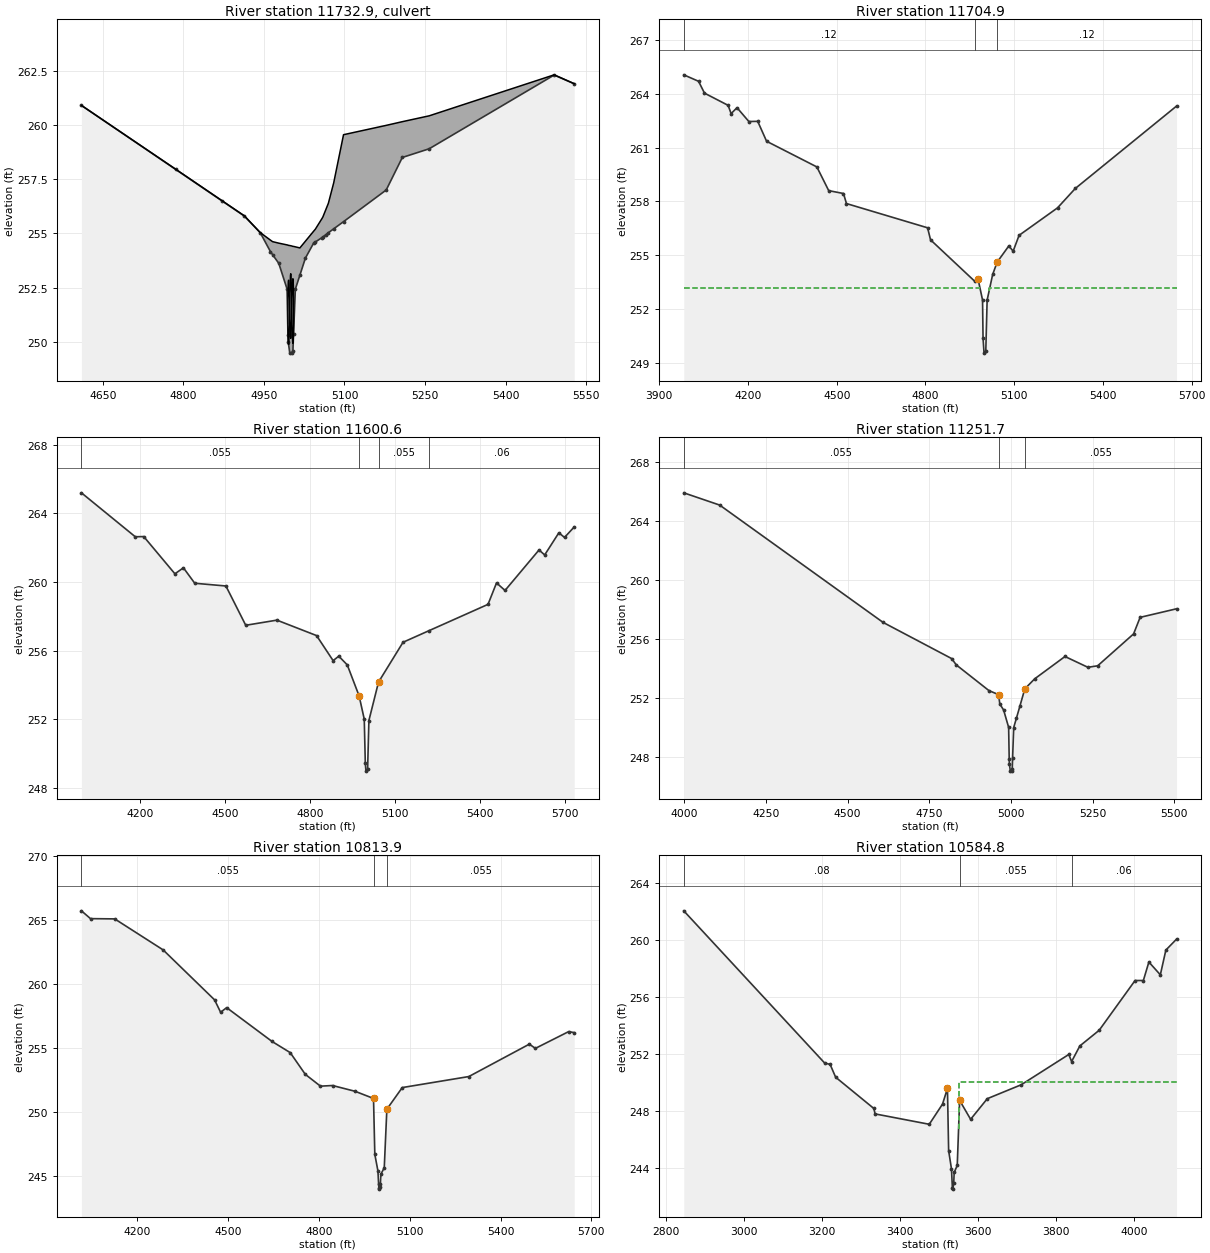
Type RM Length L Ch R = 2 ,11732.9 ,,,
BEGIN DESCRIPTION:
IRONWOOD
Structure ID: K166-01-00-S18
Three conc pipes are staggered and proj from fill 11/15/2 VRR
END DESCRIPTION:
Bridge Culvert--1,0,-1,-1, 0
Deck Dist Width WeirC Skew NumUp NumDn MinLoCord MaxHiCord MaxSubmerge Is_Ogee
2,46,2.6,0, 31, 31, 254, , .95, 0, ,,,
  4610.2  4785.7  4872.5  4913.6    4943  4962.2  4966.1  4977.7  4993.1  4994.8
  4995.4  4998.2  5001.9  5004.1  5005.2  5008.6    5017  5027.3  5042.6  5045.7
  5057.8  5059.7  5065.4  5070.1    5080  5098.3  5177.8  5207.8  5257.8  5490.6
  5527.9
   260.9  257.96   256.5  255.81  255.04  254.69  254.62  254.55  254.47  254.46
  254.45  254.44  254.42   254.4   254.4  254.38  254.33  254.64   255.1  255.19
  255.67  255.75   256.1  256.39  257.33  259.55  259.98  260.15  260.42  262.31
   261.9
   260.9  257.95  256.49   255.8  255.04  254.16  254.02  253.62  252.44  250.32
  249.98  249.48  249.48   249.6  250.36  252.43  253.07  253.86  254.55   254.6
   254.8  254.83  254.94  255.03  255.21  255.54     257   258.5   258.9   262.3
   261.9
  4610.2  4785.7  4872.5  4913.6    4943  4962.2  4966.1  4977.7  4993.1  4994.8
  4995.4  4998.2  5001.9  5004.1  5005.2  5008.6    5017  5027.3  5042.6  5045.7
  5057.8  5059.7  5065.4  5070.1    5080  5098.3  5177.8  5207.8  5257.8  5490.6
  5527.9
   260.9  257.96   256.5  255.81  255.04  254.69  254.62  254.55  254.47  254.46
  254.45  254.44  254.42   254.4   254.4  254.38  254.33  254.64   255.1  255.19
  255.67  255.75   256.1  256.39  257.33  259.55  259.98  260.15  260.42  262.31
   261.9
   260.9  257.95  256.49   255.8  255.04  254.16  254.02  253.62  252.44  250.32
  249.98  249.48  249.48   249.6  250.36  252.43  253.07  253.86  254.55   254.6
   254.8  254.83  254.94  255.03  255.21  255.54     257   258.5   258.9   262.3
   261.9
BR Coef= 1 , 0 , 0 ,1.25, 0 ,,,.8,0,2,0,
WSPro=,,,, 1 ,,,, 0 ,,,, 0 ,,,,-1 ,-1 ,-1 , 0 , 0 , 0 , 0 , 0
Culvert=1,3,,46,.015,.5,1,1,3,249.86,4996,249.06,4996,Culvert #1  , 0 ,10
Culvert Bottom n=.015
Culvert=1,3,,46,.015,.5,1,1,3,250.15,5000,249.45,5000,Culvert #2  , 0 ,10
Culvert Bottom n=.015
Culvert=1,3,,46,.015,.5,1,1,3,249.92,5004,249.23,5004,Culvert #3  , 0 ,10
Culvert Bottom n=.015
BR U #Sta/Elev= 31
  4610.2   260.9  4785.7  257.95  4872.5  256.49  4913.6   255.8    4943  255.04
  4962.2  254.16  4966.1  254.02  4977.7  253.62  4993.1  252.44  4994.8  250.32
  4995.4  249.98  4998.2  249.48  5001.9  249.48  5004.1   249.6  5005.2  250.36
  5008.6  252.43    5017  253.07  5027.3  253.86  5042.6  254.55  5045.7   254.6
  5057.8   254.8  5059.7  254.83  5065.4  254.94  5070.1  255.03    5080  255.21
  5098.3  255.54  5177.8     257  5207.8   258.5  5257.8   258.9  5490.6   262.3
  5527.9   261.9
BR U #Mann= 4
  4610.2     .12    4943     .08  5065.4     .12  5490.6     .99
BR D #Sta/Elev= 31
  4610.2   260.9  4785.7  257.95  4872.5  256.49  4913.6   255.8    4943  255.04
  4962.2  254.16  4966.1  254.02  4977.7  253.62  4993.1  252.44  4994.8  250.32
  4995.4  249.98  4998.2  249.48  5001.9  249.48  5004.1   249.6  5005.2  250.36
  5008.6  252.43    5017  253.07  5027.3  253.86  5042.6  254.55  5045.7   254.6
  5057.8   254.8  5059.7  254.83  5065.4  254.94  5070.1  255.03    5080  255.21
  5098.3  255.54  5177.8     257  5207.8   258.5  5257.8   258.9  5490.6   262.3
  5527.9   261.9
BR D #Mann= 4
  4610.2     .12    4943     .08  5065.4     .12  5490.6     .99
BC Design=,, 0 ,, 0 ,,,,,,
BC HTab HWMax=264.54

Type RM Length L Ch R = 1 ,11704.9 ,89.6,104.3,124.7
BEGIN DESCRIPTION:
K166-01-00-S18_IRONWOOD-XS2
Moved channel banks back to surveyed channel banks by JJA on 3/14/03.
Lowered channel roughness from 0.08 to 0.05 to aid in the fixing of crossing profiles. - JJA 3/17/02
END DESCRIPTION:
XS GIS Cut Line= 6
      2943606.12      13946546.9      2942921.86      13946909.4
      2942770.46      13947054.1      2942707.55      13947125.3
      2942694.51      13947157.6      2942665.57      13947709.2
#Sta/Elev= 30
    3983  265.05    4033  264.69    4053  264.03    4133  263.35    4143  262.89
    4163  263.22    4203  262.45    4233  262.46    4263  261.35    4433  259.92
    4473   258.6    4523  258.44    4533  257.88  4807.3  256.53  4817.3  255.86
  4966.8  253.55  4977.7  253.69  4993.1  252.51  4994.8  250.39  4998.2  249.55
  5004.1  249.67  5008.6   252.5  5027.3  253.93  5042.6  254.62  5081.9  255.52
  5096.6  255.23  5116.6  256.11  5246.6  257.64  5306.6  258.72    5649  263.31
#Mann= 3 ,-1 , 0
    3983     .12       0  4966.8     .08       0  5042.6     .12       0
#XS Ineff= 2 , 0
       0 4984.49   253.2  5015.5       0   253.2
Permanent Ineff=
       F       F
Bank Sta=4977.7,5042.6
XS Rating Curve= 0
Exp/Cntr=.5,.3

Type RM Length L Ch R = 1 ,11600.6 ,349.9,348.9,340.2
BEGIN DESCRIPTION:
K166-01-00-S18_IRONWOOD-XS1
LIDAR overbanks, interpolated channel
END DESCRIPTION:
XS GIS Cut Line= 4
       2943485.3     13946345.73      2942812.81      13946926.3
      2942624.99     13947012.89      2942584.62      13947655.8
#Sta/Elev= 30
  3993.9  265.19  4183.9  262.63  4213.9  262.64  4323.9  260.47  4353.9  260.82
  4393.9  259.92  4503.9  259.76  4573.9  257.47  4683.9  257.77  4823.9  256.87
  4882.3  255.41  4902.3  255.67  4932.3  255.16 4974.13  253.35 4992.21     252
 4995.93  249.43  4998.2  248.97  5004.1  249.09  5008.6  251.92  5042.6  254.16
  5129.1  256.48    5220  257.15  5429.1  258.69  5459.1  259.94  5489.1   259.5
  5609.1  261.86  5629.1  261.57  5679.1  262.86  5699.1  262.59  5733.3   263.2
#Mann= 4 ,-1 , 0
  3993.9    .055       0 4974.13     .05       0  5042.6    .055       0
    5220     .06       0
Bank Sta=4974.13,5042.6
XS Rating Curve= 0
Exp/Cntr=.3,.1

Type RM Length L Ch R = 1 ,11251.7 ,437.5,437.8,436.6
BEGIN DESCRIPTION:
INTERPOLATEDX-SECTION
END DESCRIPTION:
XS GIS Cut Line= 4
      2943459.12      13946128.7      2942738.37      13946548.9
      2942466.59      13946740.8      2942317.81      13947048.2
#Sta/Elev= 27
  3998.6  265.89  4108.6  265.06  4608.6  257.12  4818.6  254.67  4832.9  254.24
  4932.9   252.5  4962.2  252.23  4966.1  251.59  4977.7  251.19  4993.1  250.01
  4994.8  247.89  4995.4  247.55  4998.2  247.05  5001.9  247.05  5004.1  247.17
  5005.2  247.93  5008.6     250    5017  250.64  5027.3  251.43  5042.6  252.62
  5072.9   253.3  5165.6  254.81  5235.6  254.08  5265.6  254.18  5375.6  256.34
  5395.6  257.46  5507.1  258.04
#Mann= 3 ,-1 , 0
  3998.6    .055       0  4962.2     .05       0  5042.6    .055       0
Bank Sta=4962.2,5042.6
XS Rating Curve= 0
Exp/Cntr=.3,.1

Type RM Length L Ch R = 1 ,10813.9 ,251.8,229.1,155.4
BEGIN DESCRIPTION:
INTERPOLATEDX-SECTION2-XS4
END DESCRIPTION:
XS GIS Cut Line= 4
      2943240.27      13945752.9      2942519.52      13946173.1
      2942334.82      13946303.5      2942310.01      13946871.3
#Sta/Elev= 30
  4014.8  265.72  4044.8  265.11  4124.8  265.09  4284.8  262.67  4454.8  258.77
  4474.8   257.8  4494.8  258.16  4644.8  255.52  4704.8  254.65  4754.8  252.95
  4804.8  252.03  4844.8  252.08  4919.1  251.63  4980.2  251.07  4984.5   246.7
  4994.8  245.41    4997   244.4  4998.1  244.07  4999.6  243.99  5001.5  244.13
  5002.9  244.42  5004.6  245.16  5015.7  245.66  5024.3  250.23  5075.2  251.92
  5295.2  252.78  5495.2  255.31  5515.2  254.98  5625.2  256.29  5643.5  256.21
#Mann= 3 ,-1 , 0
  4014.8    .055       0  4980.2     .08       0  5024.3    .055       0
Bank Sta=4980.2,5024.3
XS Rating Curve= 0
Exp/Cntr=.5,.3

Type RM Length L Ch R = 1 ,10584.8 ,343.2,98.1,145.5
BEGIN DESCRIPTION:
K166-01-00-S17_FIELDSTORERD-XS3
Moved ineffective areas to proper locatlions at the culvert edges. --JJA 3/14/03
END DESCRIPTION:
XS GIS Cut Line= 4
      2942976.08     13945601.79      2942308.77      13945770.7
       2942287.1     13946476.38      2941995.43     13946733.33
#Sta/Elev= 30
2846.317  262.06 3206.94  251.363221.083  251.263235.225  250.363333.089  248.16
  3336.2  247.783474.935  247.053508.947  248.473521.533  249.573524.574   245.2
3531.857  243.91 3534.19  242.573535.251  242.493537.584  242.923538.787  243.66
3546.635  244.163552.716  248.733580.859   247.43623.569  248.853710.543  249.83
3832.307  251.963839.448  251.463860.591  252.563910.088  253.664002.012  257.16
4023.226  257.164037.368  258.464066.713  257.564080.855   259.3 4108.22  260.07
#Mann= 3 ,-1 , 0
2846.317     .08       03552.716    .055       03839.448     .06       0
#XS Ineff= 2 , 0
       03520.981   248.43550.015       0     250
Permanent Ineff=
       F       T
Bank Sta=3521.533,3552.716
XS Rating Curve= 0
Skew Angle= 45
Exp/Cntr=.5,.3