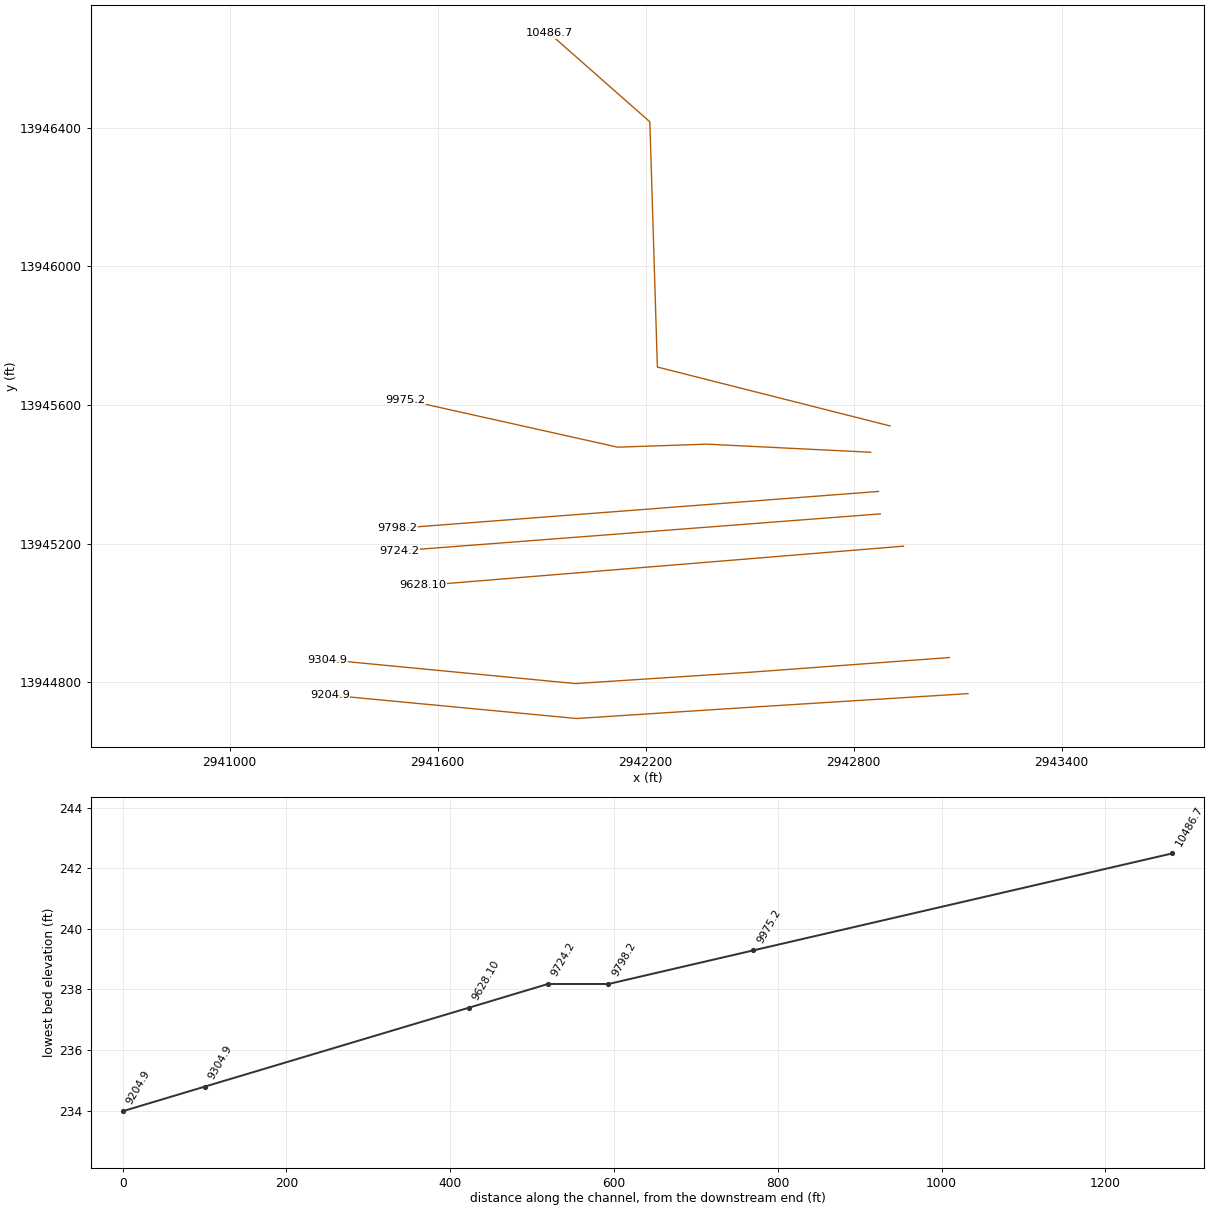
HEC-RAS study K166-01-00.prj: K166-01-00

--- K166-01-00.g01 (geometry) --- (continued)

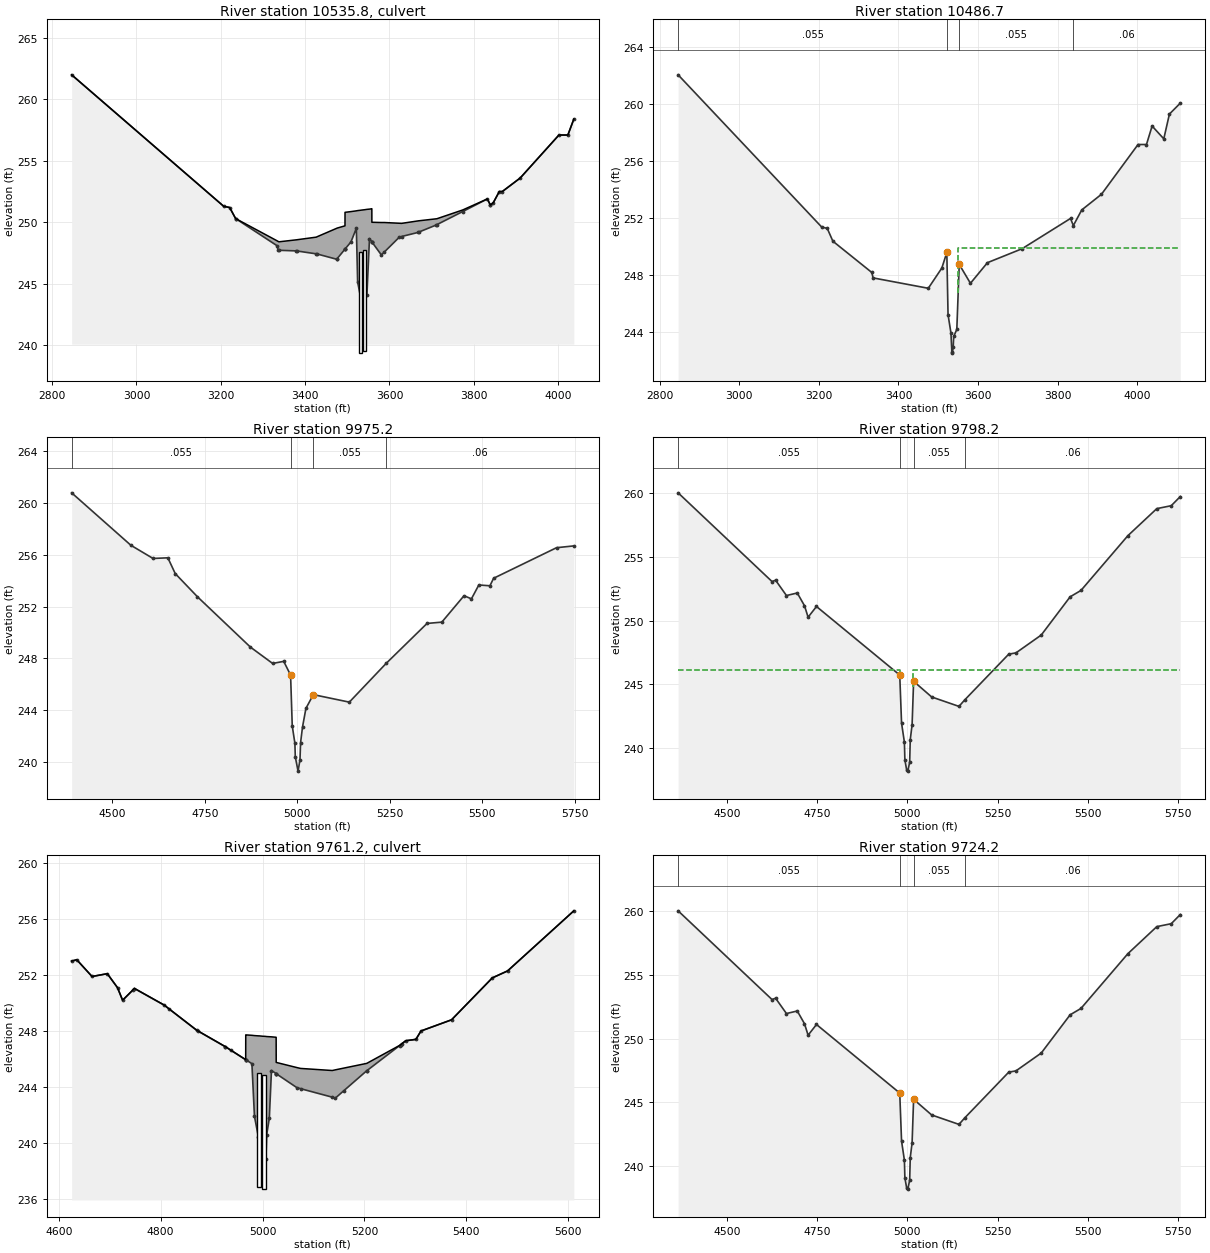
Type RM Length L Ch R = 2 ,10535.8 ,,,
BEGIN DESCRIPTION:
FIELD STORE RD; D/S end has 45 degree box culvert
U/S end has 90 degree culverts but staggered by approx. one foot 11/15/2 VRR
Structure ID: K166-01-00-S17
END DESCRIPTION:
Bridge Culvert--1,0,-1,-1, 0
Deck Dist Width WeirC Skew NumUp NumDn MinLoCord MaxHiCord MaxSubmerge Is_Ogee
10,74,2.6,45, 52, 52, , , .95, 0, ,,,
2846.317 3206.943221.0833235.2253235.2893333.089  3336.23337.897 3378.913381.173
3426.4983428.2663474.9353476.2783494.5843494.6633494.7413508.9473521.5333524.574
3531.8573533.413 3534.193535.2513536.5943537.5843537.7973538.7873546.6353552.716
3558.2253558.3033558.3813580.8593588.2843623.5693628.8013667.5513669.6723710.543
3712.7353773.6873832.3073839.3783839.4483846.4493860.5913867.6623910.0884002.012
4023.2264037.368
     262   251.3   251.2   250.3   250.3   248.5  248.44  248.41  248.57  248.58
  248.79  248.82  249.51  249.53  249.71  250.81  250.81  250.87  250.93  250.95
  250.98  250.99  250.99     251     251  251.01  251.01  251.01  251.05  251.07
   251.1   251.1     250  249.98  249.98  249.92  249.91  250.11  250.12  250.28
  250.29     251   251.9   251.4   251.4   251.6   252.5   252.5   253.6   257.1
   257.1   258.4
     262   251.3   251.2   250.3   250.3   248.1  247.72  247.72  247.67  247.66
  247.43  247.42  246.99  247.05  247.81  247.81  247.82  248.41  249.51  245.14
  243.85  242.84  242.51  242.43  242.57  242.86  242.98   243.6   244.1  248.67
  248.41  248.41   248.4  247.34  247.59  248.79  248.84  249.17   249.2  249.77
  249.81  250.87   251.9   251.4   251.4   251.6   252.5   252.5   253.6   257.1
   257.1   258.4
2846.317 3206.943221.0833235.2253235.2893333.089  3336.23337.897 3378.913381.173
3426.4983428.2663474.9353476.2783494.5843494.6633494.7413508.9473521.5333524.574
3531.8573533.413 3534.193535.2513536.5943537.5843537.7973538.7873546.6353552.716
3558.2253558.3033558.3813580.8593588.2843623.5693628.8013667.5513669.6723710.543
3712.7353773.6873832.3073839.3783839.4483846.4493860.5913867.6623910.0884002.012
4023.2264037.368
     262   251.3   251.2   250.3   250.3   248.5  248.44  248.41  248.57  248.58
  248.79  248.82  249.51  249.53  249.71  250.81  250.81  250.87  250.93  250.95
  250.98  250.99  250.99     251     251  251.01  251.01  251.01  251.05  251.07
   251.1   251.1     250  249.98  249.98  249.92  249.91  250.11  250.12  250.28
  250.29     251   251.9   251.4   251.4   251.6   252.5   252.5   253.6   257.1
   257.1   258.4
     262   251.3   251.2   250.3   250.3   248.1  247.72  247.72  247.67  247.66
  247.43  247.42  246.99  247.05  247.81  247.81  247.82  248.41  249.51  245.14
  243.85  242.84  242.51  242.43  242.57  242.86  242.98   243.6   244.1  248.67
  248.41  248.41   248.4  247.34  247.59  248.79  248.84  249.17   249.2  249.77
  249.81  250.87   251.9   251.4   251.4   251.6   252.5   252.5   253.6   257.1
   257.1   258.4
BR Coef= 1 , 0 , 0 ,1.25, 0 ,,,.8,-1,2,0,
WSPro=,,,, 1 ,,,, 0 ,,,, 0 ,,,,-1 ,-1 ,-1 , 0 , 0 , 0 , 0 , 0
Culvert=2,8.2,8,74,.015,.7,.65,8,3,239.35,3530.867,239.26,3530.867,Culvert #1  , 0 ,10
Culvert Bottom n=.015
Culvert=2,8.2,8,74,.015,.7,.65,8,3,239.56,3540.13,239.33,3540.13,Culvert #2  , 0 ,10
Culvert Bottom n=.015
BR U #Sta/Elev= 52
2846.317     262 3206.94   251.33221.083   251.23235.225   250.33235.289   250.3
3333.089   248.1  3336.2  247.723337.897  247.72 3378.91  247.673381.173  247.66
3426.498  247.433428.266  247.423474.935  246.993476.278  247.053494.584  247.81
3494.663  247.813494.741  247.823508.947  248.413521.533  249.513524.574  245.14
3531.857  243.853533.413  242.84 3534.19  242.513535.251  242.433536.594  242.57
3537.584  242.863537.797  242.983538.787   243.63546.635   244.13552.716  248.67
3558.225  248.413558.303  248.413558.381   248.43580.859  247.343588.284  247.59
3623.569  248.793628.801  248.843667.551  249.173669.672   249.23710.543  249.77
3712.735  249.813773.687  250.873832.307   251.93839.378   251.43839.448   251.4
3846.449   251.63860.591   252.53867.662   252.53910.088   253.64002.012   257.1
4023.226   257.14037.368   258.4
BR U #Mann= 4
2846.317    .0553521.533     .083552.716    .0553839.448     .06
BR U Banks=3521.533,3552.716
BR D #Sta/Elev= 52
2846.317     262 3206.94   251.33221.083   251.23235.225   250.33235.289   250.3
3333.089   248.1  3336.2  247.723337.897  247.72 3378.91  247.673381.173  247.66
3426.498  247.433428.266  247.423474.935  246.993476.278  247.053494.584  247.81
3494.663  247.813494.741  247.823508.947  248.413521.533  249.513524.574  245.14
3531.857  243.853533.413  242.84 3534.19  242.513535.251  242.433536.594  242.57
3537.584  242.863537.797  242.983538.787   243.63546.635   244.13552.716  248.67
3558.225  248.413558.303  248.413558.381   248.43580.859  247.343588.284  247.59
3623.569  248.793628.801  248.843667.551  249.173669.672   249.23710.543  249.77
3712.735  249.813773.687  250.873832.307   251.93839.378   251.43839.448   251.4
3846.449   251.63860.591   252.53867.662   252.53910.088   253.64002.012   257.1
4023.226   257.14037.368   258.4
BR D #Mann= 4
2846.317    .0553521.533     .083552.716    .0553839.448     .06
BR D Banks=3521.533,3552.716
BC Design=,, 0 ,, 0 ,,,,,,
BC HTab HWMax=262.06

Type RM Length L Ch R = 1 ,10486.7 ,223.5,511.5,544.3
BEGIN DESCRIPTION:
K166-01-00-S17_FIELDSTORERD-XS2
Moved ineffective areas to proper locatlions at the culvert edges. --JJA 3/14/03
END DESCRIPTION:
XS GIS Cut Line= 4
      2942904.81     13945539.92      2942233.84     13945709.75
      2942212.12     13946417.04      2941922.08     13946672.55
#Sta/Elev= 30
2846.317  262.06 3206.94  251.363221.083  251.263235.225  250.363333.089  248.16
  3336.2  247.783474.935  247.053508.947  248.473521.533  249.573524.574   245.2
3531.857  243.91 3534.19  242.573535.251  242.493537.584  242.923538.787  243.66
3546.635  244.163552.716  248.733580.859   247.43623.569  248.853710.543  249.83
3832.307  251.963839.448  251.463860.591  252.563910.088  253.664002.012  257.16
4023.226  257.164037.368  258.464066.713  257.564080.855   259.3 4108.22  260.07
#Mann= 4 ,-1 , 0
2846.317    .055       03521.533     .05       03552.716    .055       0
3839.448     .06       0
#XS Ineff= 2 , 0
       03520.981   248.33550.015       0   249.9
Permanent Ineff=
       F       F
Bank Sta=3521.533,3552.716
XS Rating Curve= 0
Skew Angle= 45
Exp/Cntr=.5,.3

Type RM Length L Ch R = 1 ,9975.2  ,178.8,177,186.2
BEGIN DESCRIPTION:
K166-01-00-S16_TAYLOR-XS4
LIDAR overbanks, interpolated channel
END DESCRIPTION:
XS GIS Cut Line= 4
      2942849.15     13945463.95      2942376.52     13945487.32
      2942119.36     13945478.63      2941507.59     13945615.11
#Sta/Elev= 30
    4390  260.79    4550  256.74    4610  255.72    4650  255.77    4670  254.55
    4730  252.76  4873.2  248.87  4933.2  247.61  4963.2  247.77 4981.73  246.71
 4986.23  242.78 4993.34  241.45 4994.51  240.39  5001.9  239.29 5007.12  240.15
 5008.75  241.49 5013.97   242.7  5023.2  244.14  5043.2   245.2  5140.5  244.62
    5240 247.612  5350.5   250.7  5390.5   250.8  5450.5  252.84  5470.5   252.6
  5490.5  253.67  5520.5  253.61  5530.5  254.19  5700.5  256.55  5747.3  256.69
#Mann= 4 ,-1 , 0
    4390    .055       0 4981.73     .05       0  5043.2    .055       0
    5240     .06       0
Bank Sta=4981.73,5043.2
XS Rating Curve= 0
Exp/Cntr=.5,.3

Type RM Length L Ch R = 1 ,9798.2  ,65.6,74,65.1
BEGIN DESCRIPTION:
K166-01-00-S16_TAYLOR-XS3
END DESCRIPTION:
XS GIS Cut Line= 4
      2942871.64     13945350.96      2942483.81     13945321.22
      2941968.56      13945281.7      2941484.88     13945244.61
#Sta/Elev= 30
  4365.3  260.02  4625.3  253.06  4635.3  253.16  4665.3  251.96  4695.3  252.16
  4715.3  251.16  4725.3  250.26  4748.5   251.1  4979.1  245.72  4984.1  241.95
    4992  240.45  4993.3  239.07  4998.5  238.23  5001.5  238.18  5006.6  238.89
  5008.2  240.65  5013.3  241.81  5017.5  245.23  5067.5     244  5143.1  243.26
  5159.1  243.77    5281  247.36    5301  247.46    5371  248.86    5451  251.86
    5481  252.36    5611  256.66    5691  258.78    5731  259.01  5756.1  259.73
#Mann= 4 ,-1 , 0
  4365.3    .055       0  4979.1     .05       0  5017.5    .055       0
  5159.1     .06       0
#XS Ineff= 2 , 0
       0 4978.91   246.1 5016.96       0   246.1
Permanent Ineff=
       F       F
Bank Sta=4979.1,5017.5
XS Rating Curve= 0
Exp/Cntr=.5,.3

Type RM Length L Ch R = 2 ,9761.2  ,,,
BEGIN DESCRIPTION:
TAYLOR
Structure ID: K166-01-00-S16
END DESCRIPTION:
Bridge Culvert--1,0,-1,-1, 0
Deck Dist Width WeirC Skew NumUp NumDn MinLoCord MaxHiCord MaxSubmerge Is_Ogee
10,62,3,0, 49, 49, , , .95, 0, ,,,
  4625.3  4635.3  4665.3  4695.3  4715.3  4725.3  4745.3  4748.5  4807.3    4816
    4871  4872.5    4927  4927.1  4938.1 4966.89    4967 4967.11  4979.1  4984.1
    4992  4993.3  4998.5  5001.5  5003.2  5006.6  5008.2  5013.3  5017.5 5026.59
  5026.7 5026.81  5067.5  5074.6  5136.9  5143.1  5159.1  5204.4  5204.5  5269.2
    5271  5273.4    5281    5301    5311    5371    5451    5481    5611
     253   253.1   251.9   252.1   251.1   250.2  250.93  251.05  249.85   249.6
  248.05  248.02  246.88  246.88  246.62  245.95  247.72  247.72  247.69  247.67
  247.65  247.65  247.63  247.62  247.62  247.61   247.6  247.59  247.58  247.55
  247.55  245.75  245.38  245.32  245.17  245.22  245.34  245.68  245.68  246.97
  247.02  247.09   247.3   247.4     248   248.8   251.8   252.3   256.6
     253   253.1   251.9   252.1   251.1   250.2  250.92  251.04  249.84  249.59
  248.04  248.01  246.87  246.87  246.61  245.94  245.94  245.94  245.66  241.89
  240.39  239.01  238.17  238.12  238.23  238.83  240.59  241.75  245.17  244.95
  244.94  244.94  243.94  243.87  243.26   243.2  243.71  245.15  245.15  246.96
  247.01  247.08   247.3   247.4     248   248.8   251.8   252.3   256.6
  4625.3  4635.3  4665.3  4695.3  4715.3  4725.3  4745.3  4748.5  4807.3    4816
    4871  4872.5    4927  4927.1  4938.1 4966.89    4967 4967.11  4979.1  4984.1
    4992  4993.3  4998.5  5001.5  5003.2  5006.6  5008.2  5013.3  5017.5 5026.59
  5026.7 5026.81  5067.5  5074.6  5136.9  5143.1  5159.1  5204.4  5204.5  5269.2
    5271  5273.4    5281    5301    5311    5371    5451    5481    5611
     253   253.1   251.9   252.1   251.1   250.2  250.93  251.05  249.85   249.6
  248.05  248.02  246.88  246.88  246.62  245.95  247.72  247.72  247.69  247.67
  247.65  247.65  247.63  247.62  247.62  247.61   247.6  247.59  247.58  247.55
  247.55  245.75  245.38  245.32  245.17  245.22  245.34  245.68  245.68  246.97
  247.02  247.09   247.3   247.4     248   248.8   251.8   252.3   256.6
     253   253.1   251.9   252.1   251.1   250.2  250.92  251.04  249.84  249.59
  248.04  248.01  246.87  246.87  246.61  245.94  245.94  245.94  245.66  241.89
  240.39  239.01  238.17  238.12  238.23  238.83  240.59  241.75  245.17  244.95
  244.94  244.94  243.94  243.87  243.26   243.2  243.71  245.15  245.15  246.96
  247.01  247.08   247.3   247.4     248   248.8   251.8   252.3   256.6
BR Coef= 1 , 0 , 0 ,1.25, 0 ,,,.8,0,2,0,
WSPro=,,,, 1 ,,,, 0 ,,,, 0 ,,,,-1 ,-1 ,-1 , 0 , 0 , 0 , 0 , 0
Culvert=2,8.2,8,62,.015,.7,1,8,3,236.82,4992.9,236.45,4992.9,Culvert #1  , 0 ,10
Culvert Bottom n=.015
Culvert=2,8.2,8,62,.015,.7,1,8,3,236.68,5002.9,236.49,5002.9,Culvert #2  , 0 ,10
Culvert Bottom n=.015
BR U #Sta/Elev= 49
  4625.3     253  4635.3   253.1  4665.3   251.9  4695.3   252.1  4715.3   251.1
  4725.3   250.2  4745.3  250.92  4748.5  251.04  4807.3  249.84    4816  249.59
    4871  248.04  4872.5  248.01    4927  246.87  4927.1  246.87  4938.1  246.61
 4966.89  245.94    4967  245.94 4967.11  245.94  4979.1  245.66  4984.1  241.89
    4992  240.39  4993.3  239.01  4998.5  238.17  5001.5  238.12  5003.2  238.23
  5006.6  238.83  5008.2  240.59  5013.3  241.75  5017.5  245.17 5026.59  244.95
  5026.7  244.94 5026.81  244.94  5067.5  243.94  5074.6  243.87  5136.9  243.26
  5143.1   243.2  5159.1  243.71  5204.4  245.15  5204.5  245.15  5269.2  246.96
    5271  247.01  5273.4  247.08    5281   247.3    5301   247.4    5311     248
    5371   248.8    5451   251.8    5481   252.3    5611   256.6
BR U #Mann= 4
  4625.3    .055  4979.1     .05  5017.5    .055  5159.1     .06
BR U Banks=4979.1,5017.5
BR D #Sta/Elev= 49
  4625.3     253  4635.3   253.1  4665.3   251.9  4695.3   252.1  4715.3   251.1
  4725.3   250.2  4745.3  250.92  4748.5  251.04  4807.3  249.84    4816  249.59
    4871  248.04  4872.5  248.01    4927  246.87  4927.1  246.87  4938.1  246.61
 4966.89  245.94    4967  245.94 4967.11  245.94  4979.1  245.66  4984.1  241.89
    4992  240.39  4993.3  239.01  4998.5  238.17  5001.5  238.12  5003.2  238.23
  5006.6  238.83  5008.2  240.59  5013.3  241.75  5017.5  245.17 5026.59  244.95
  5026.7  244.94 5026.81  244.94  5067.5  243.94  5074.6  243.87  5136.9  243.26
  5143.1   243.2  5159.1  243.71  5204.4  245.15  5204.5  245.15  5269.2  246.96
    5271  247.01  5273.4  247.08    5281   247.3    5301   247.4    5311     248
    5371   248.8    5451   251.8    5481   252.3    5611   256.6
BR D #Mann= 4
  4625.3    .055  4979.1     .05  5017.5    .055  5159.1     .06
BR D Banks=4979.1,5017.5
BC Design=,, 0 ,, 0 ,,,,,,
BC HTab HWMax=260.02

Type RM Length L Ch R = 1 ,9724.2  ,103.3,96.1,102.2
BEGIN DESCRIPTION:
K166-01-00-S16_TAYLOR-XS2
END DESCRIPTION:
XS GIS Cut Line= 2
      2942876.73     13945286.21      2941489.97     13945179.85
#Sta/Elev= 30
  4365.3  260.02  4625.3  253.06  4635.3  253.16  4665.3  251.96  4695.3  252.16
  4715.3  251.16  4725.3  250.26  4748.5   251.1  4979.1  245.72  4984.1  241.95
    4992  240.45  4993.3  239.07  4998.5  238.23  5001.5  238.18  5006.6  238.89
  5008.2  240.65  5013.3  241.81  5017.5  245.23  5067.5     244  5143.1  243.26
  5159.1  243.77    5281  247.36    5301  247.46    5371  248.86    5451  251.86
    5481  252.36    5611  256.66    5691  258.78    5731  259.01  5756.1  259.73
#Mann= 4 ,-1 , 0
  4365.3    .055       0  4979.1     .05       0  5017.5    .055       0
  5159.1     .06       0
#XS Ineff= 2 , 0
       0 4978.91   243.8 5016.96       0   243.8
Permanent Ineff=
       F       F
Bank Sta=4979.1,5017.5
XS Rating Curve= 0
Exp/Cntr=.5,.3

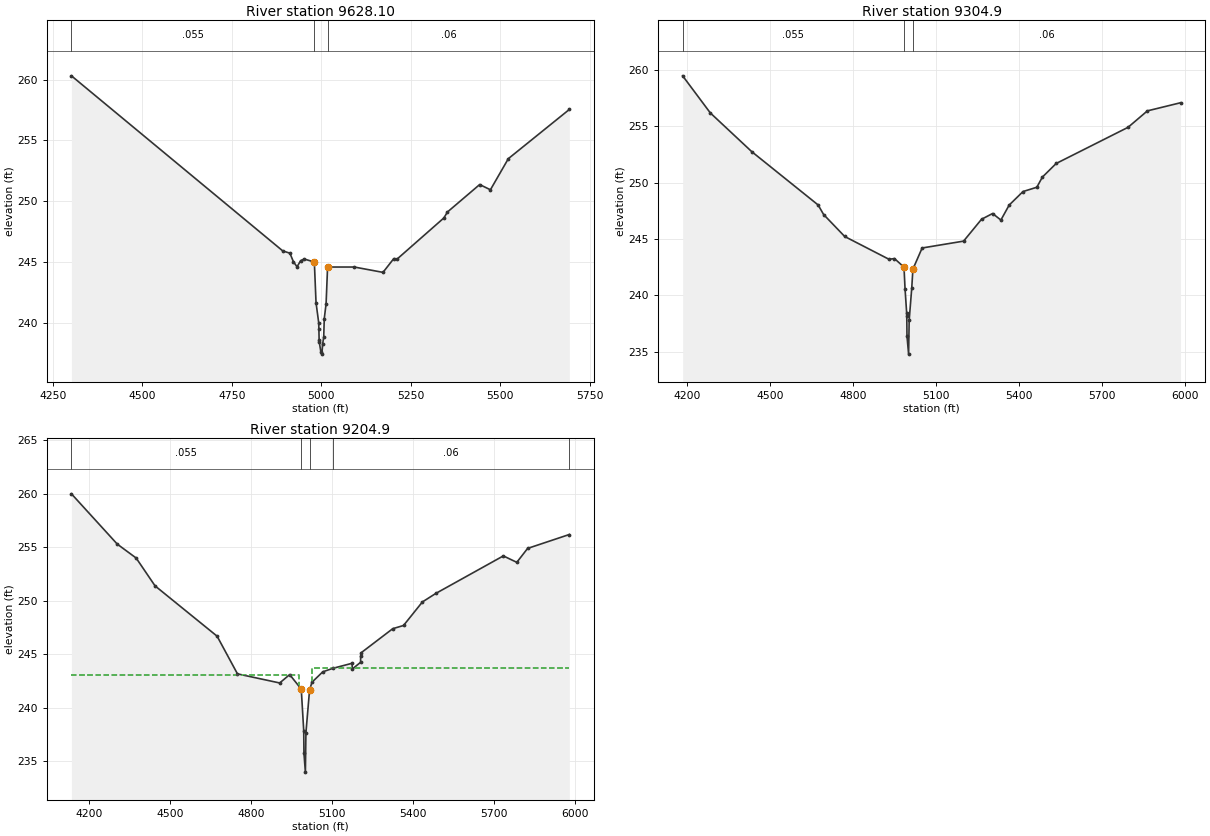
Type RM Length L Ch R = 1 ,9628.10 ,331.2,323.2,321.2
BEGIN DESCRIPTION:
K166-01-00-S16_TAYLOR-XS1
LIDAR overbanks, interpolated channel
END DESCRIPTION:
XS GIS Cut Line= 2
      2942943.63     13945193.12      2941557.98     13945079.74
#Sta/Elev= 30
  4302.1  260.31  4892.1   245.9  4912.1  245.71  4922.1     245  4932.1  244.59
  4942.1  245.09  4952.1  245.23 4980.41  244.98 4985.12  241.64 4992.56  239.99
 4993.09  239.47 4993.78  238.57 4994.06  238.42 4998.68  237.57  5001.5   237.4
 5003.57  238.23 5006.56  238.81 5008.15  240.33 5013.21  241.55 5017.39  244.57
  5092.1  244.57  5172.1  244.13  5202.1  245.26  5212.1  245.24  5342.1  248.61
  5352.1   249.1  5442.1  251.36  5472.1  250.93  5522.1  253.49  5692.4  257.54
#Mann= 3 ,-1 , 0
  4302.1    .055       0 4980.41     .04       0 5017.39     .06       0
#XS Ineff= 2 , 0
        4978.409243.66865018.799        243.7852
Permanent Ineff=
       F       F
Bank Sta=4980.41,5017.39
XS Rating Curve= 0
Exp/Cntr=.3,.1

Type RM Length L Ch R = 1 ,9304.9  ,103.2,100,100.9
BEGIN DESCRIPTION:
K166-01-00-S15_FAULKNER/MAIN-XS4
LIDAR overbanks, interpolated channel
END DESCRIPTION:
XS GIS Cut Line= 4
       2943075.9      13944871.9       2942501.2     13944829.44
      2941997.34     13944796.82      2941280.85      13944865.6
#Sta/Elev= 30
  4184.1  259.49  4284.1   256.2  4434.1  252.76  4674.1  248.03  4694.1  247.18
  4770.4  245.23  4930.4  243.21  4950.4  243.27 4984.83  242.51 4988.55  240.61
 4994.43  238.46 4994.85  238.21 4995.62   236.4  5001.5  234.79 5003.52  237.79
 5012.94  240.69 5017.02  242.33  5050.4  244.21  5200.4  244.82  5265.3  246.76
  5305.3  247.27  5335.3  246.69  5365.3  248.02  5415.3  249.22  5465.3   249.6
  5485.3   250.5  5535.3  251.71  5795.3  254.92  5865.3  256.38  5985.1   257.1
#Mann= 3 ,-1 , 0
  4184.1    .055       0 4984.83     .04       0 5017.02     .06       0
Bank Sta=4984.83,5017.02
XS Rating Curve= 0
Exp/Cntr=.5,.3

Type RM Length L Ch R = 1 ,9204.9  ,53.8,54,52.6
BEGIN DESCRIPTION:
K166-01-00-S15_FAULKNER/MAIN-XS3
END DESCRIPTION:
XS GIS Cut Line= 4
      2943129.67     13944767.82      2942504.67     13944728.66
      2942000.82     13944696.04      2941289.39     13944763.48
#Sta/Elev= 30
  4134.2  259.98  4304.2  255.28  4374.2  253.98  4444.2  251.38  4674.2  246.68
  4749.7  243.16  4906.2  242.31  4943.2  243.09  4986.2  241.74  4995.4  237.82
  4996.1  235.77  5001.5  233.98  5003.5  237.66  5016.9  241.64  5025.9  242.38
  5065.9  243.35  5103.8  243.68  5174.8  244.15  5175.2  243.61  5206.1  244.24
  5206.3  244.82  5209.2  245.15  5325.3  247.38  5365.3  247.68  5435.3  249.88
  5485.3  250.68  5735.3  254.18  5785.3  253.58  5825.3  254.88  5979.9  256.18
#Mann= 5 ,-1 , 0
  4134.2    .055       0  4986.2     .04       0  5016.9    .055       0
  5103.8     .06       0  5979.9     .99       0
#XS Ineff= 2 , 0
       0  4976.2  243.09  5026.9       0  243.72
Permanent Ineff=
       F       F
Bank Sta=4986.2,5016.9
XS Rating Curve= 0
Exp/Cntr=.5,.3