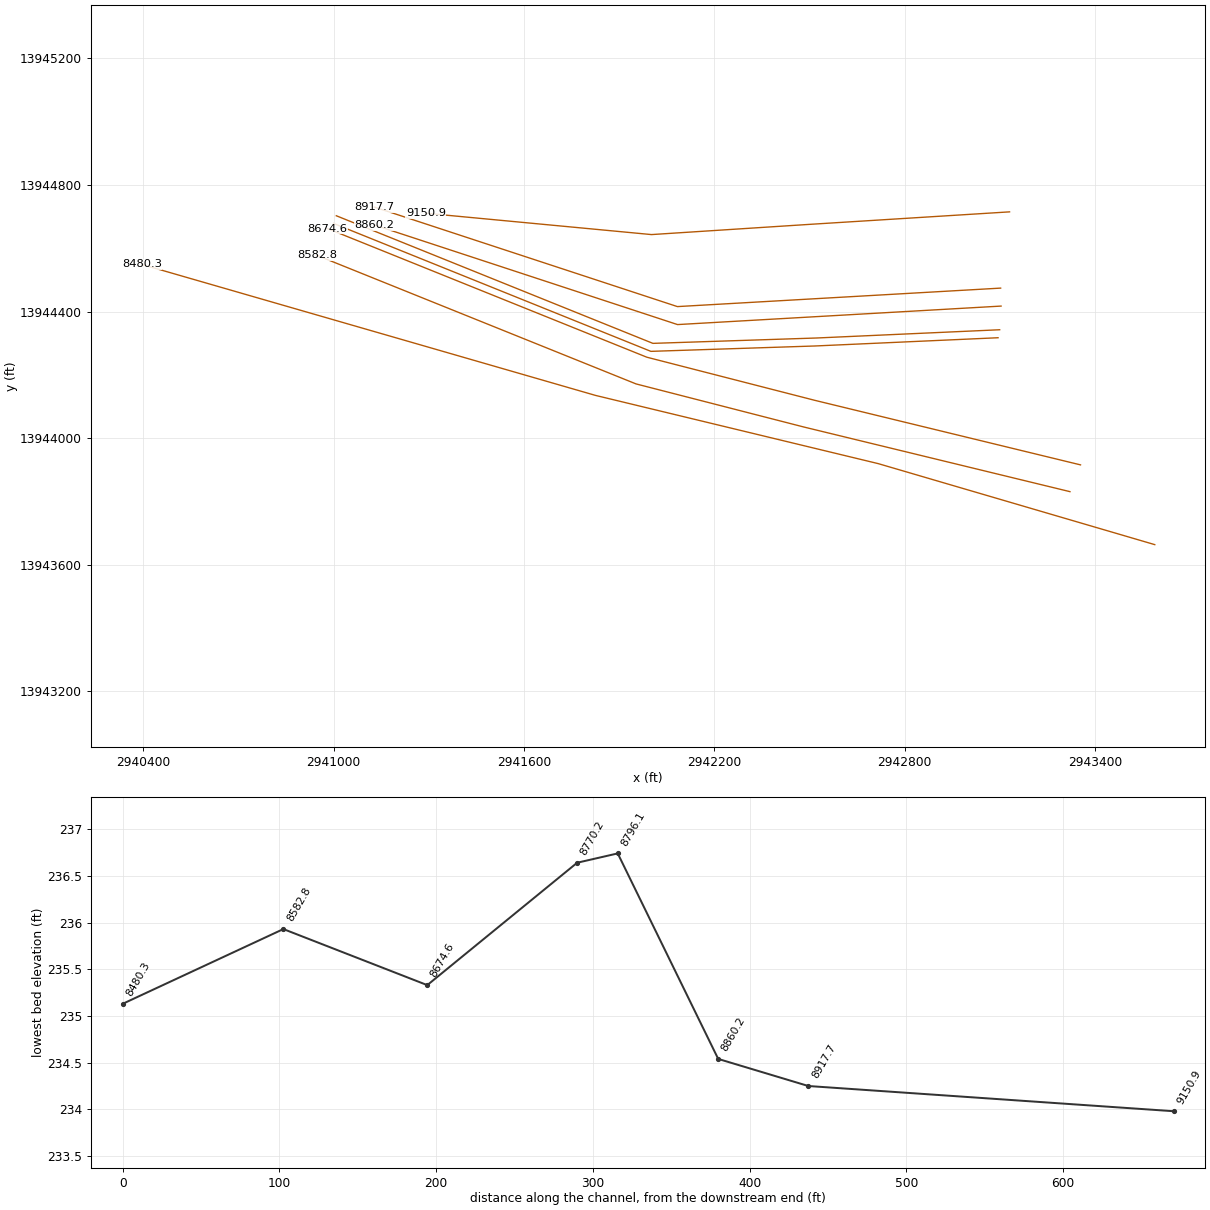
HEC-RAS study K166-01-00.prj: K166-01-00

--- K166-01-00.g01 (geometry) --- (continued)

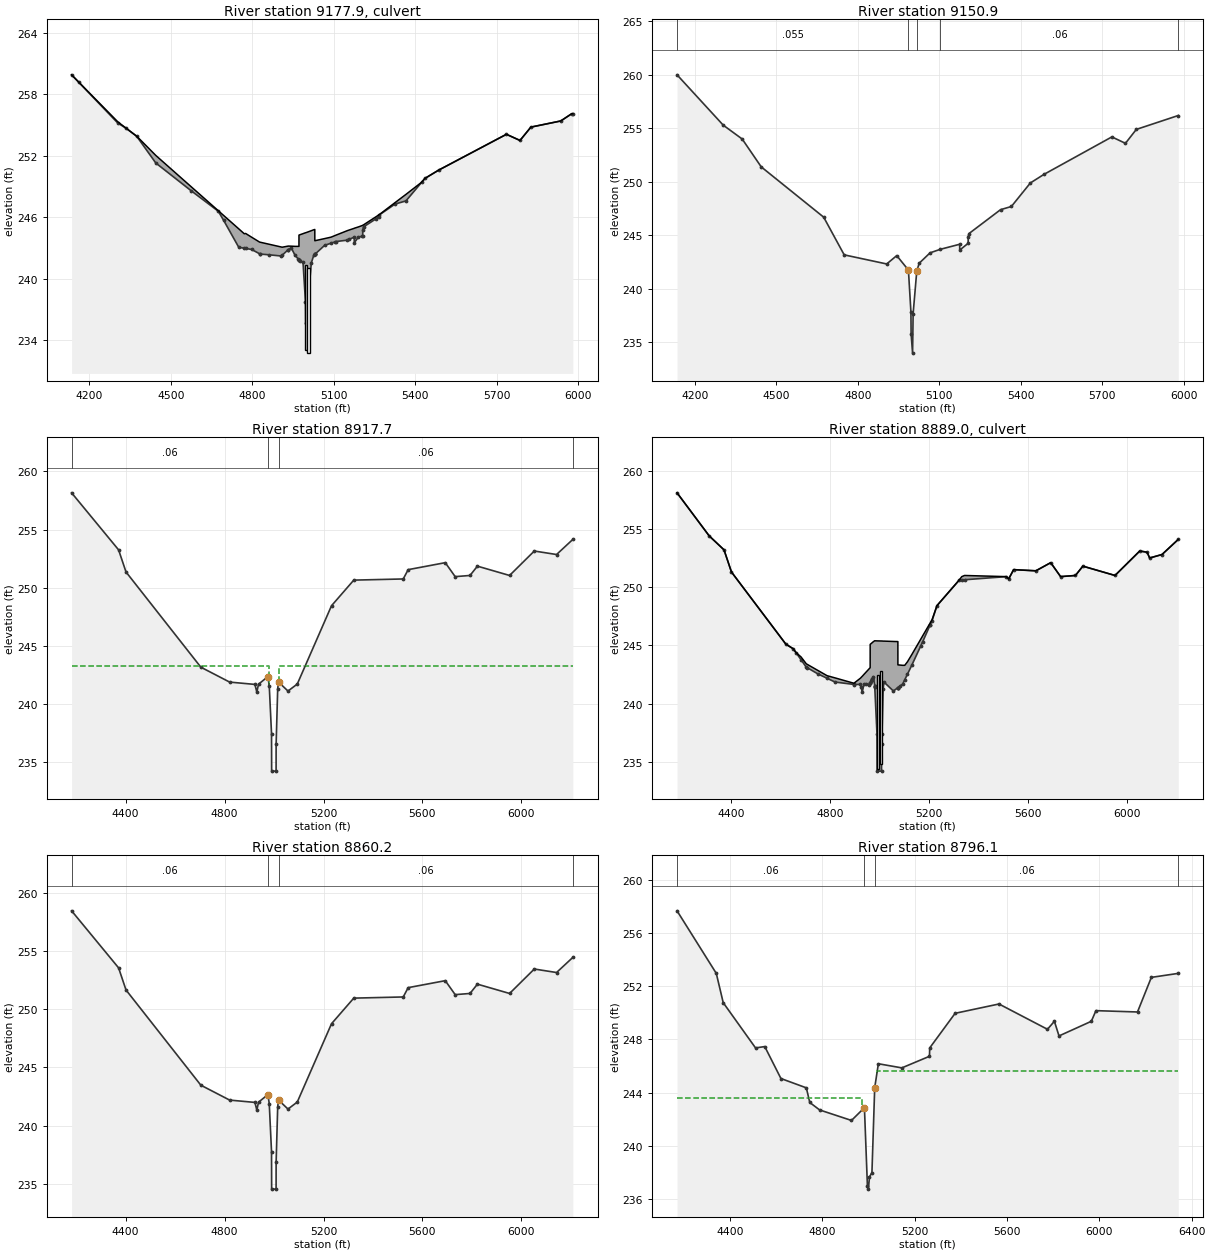
Type RM Length L Ch R = 2 ,9177.9  ,,,
BEGIN DESCRIPTION:
FAULKNER / MAIN
Structure ID: K166-01-00-S15
Metal pipe crossing directly in front of culvert about 0.5' diameter 11/15/2 VRR
END DESCRIPTION:
Bridge Culvert--1,0,-1,-1, 0
Deck Dist Width WeirC Skew NumUp NumDn MinLoCord MaxHiCord MaxSubmerge Is_Ogee
10,34,3,0, 52, 52, , , .95, 0, ,,,
  4134.2  4304.2  4334.2  4374.2  4444.2  4674.2  4749.7    4770    4775  4796.8
  4826.3  4906.2  4909.6    4932  4943.2  4957.1 4971.29  4971.4  4976.5  4986.2
  4995.4  4996.1  5001.5  5003.5  5004.5  5016.9  5025.9  5029.7 5029.81  5065.9
  5089.5  5108.1    5150  5174.8  5175.2  5190.5  5206.1  5206.3  5209.2    5265
  5265.3  5325.3  5365.3  5422.8  5435.3  5485.3  5735.3  5785.3  5825.3  5935.3
  5975.3  5979.9
   259.9  255.32  254.71  253.91  252.04  246.65  244.88   244.4  244.43  244.07
  243.59  243.11  243.09   243.2  243.19  243.17  243.17  244.27  244.32  244.41
   244.5   244.5  244.55  244.57  244.58   244.7  244.79  244.82  243.72  243.93
  244.07  244.27  244.71  244.93  244.94  245.07  245.22  245.23  245.27  246.23
  246.23  247.44  248.24  249.42   249.8   250.6   254.1   253.5   254.8   255.4
   256.1   256.1
   259.9   255.2   254.7   253.9   251.3   246.6  243.08  242.99  242.97  242.87
  242.45  242.23  242.31  242.85  243.01  242.29  241.87  241.86  241.71  241.66
  237.74  235.69   233.9  237.58  237.82  241.56   242.3  242.39  242.39  243.27
  243.48  243.64  243.78  244.07  243.53  244.08  244.16  244.74  245.07  246.03
   246.2   247.3   247.6  249.41   249.8   250.6   254.1   253.5   254.8   255.4
   256.1   256.1
  4134.2  4304.2  4334.2  4374.2  4444.2  4674.2  4749.7    4770    4775  4796.8
  4826.3  4906.2  4909.6    4932  4943.2  4957.1 4971.29  4971.4  4976.5  4986.2
  4995.4  4996.1  5001.5  5003.5  5004.5  5016.9  5025.9  5029.7 5029.81  5065.9
  5089.5  5108.1    5150  5174.8  5175.2  5190.5  5206.1  5206.3  5209.2    5265
  5265.3  5325.3  5365.3  5422.8  5435.3  5485.3  5735.3  5785.3  5825.3  5935.3
  5975.3  5979.9
   259.9  255.32  254.71  253.91  252.04  246.65  244.88   244.4  244.43  244.07
  243.59  243.11  243.09   243.2  243.19  243.17  243.17  244.27  244.32  244.41
   244.5   244.5  244.55  244.57  244.58   244.7  244.79  244.82  243.72  243.93
  244.07  244.27  244.71  244.93  244.94  245.07  245.22  245.23  245.27  246.23
  246.23  247.44  248.24  249.42   249.8   250.6   254.1   253.5   254.8   255.4
   256.1   256.1
   259.9   255.2   254.7   253.9   251.3   246.6  243.08  242.99  242.97  242.87
  242.45  242.23  242.31  242.85  243.01  242.29  241.87  241.86  241.71  241.66
  237.74  235.69   233.9  237.58  237.82  241.56   242.3  242.39  242.39  243.27
  243.48  243.64  243.78  244.07  243.53  244.08  244.16  244.74  245.07  246.03
   246.2   247.3   247.6  249.41   249.8   250.6   254.1   253.5   254.8   255.4
   256.1   256.1
BR Coef= 1 , 0 , 0 ,1.25, 0 ,,,.8,0,2,0,
WSPro=,,,, 1 ,,,, 0 ,,,, 0 ,,,,-1 ,-1 ,-1 , 0 , 0 , 0 , 0 , 0
Culvert=2,8.3,8,34,.013,.7,1,8,3,233.05,4996.7,233.08,4996.7,Culvert #1  , 0 ,10
Culvert Bottom n=.013
Culvert=2,8.3,8,34,.013,.7,1,8,3,232.76,5006.2,233.18,5006.2,Culvert #2  , 0 ,10
Culvert Bottom n=.013
BR U #Sta/Elev= 66
  4134.2   259.9    4160  259.19  4304.2   255.2  4334.2   254.7  4374.2   253.9
  4444.2   251.3  4574.2   248.6  4674.2   246.6  4694.2   245.7  4749.7  243.08
    4770  242.99    4775  242.97  4796.8  242.87  4826.3  242.45  4828.7  242.42
  4860.7  242.35  4906.2  242.23  4909.6  242.31    4932  242.85  4932.8  242.86
  4943.2  243.01  4957.1  242.29  4969.2  241.93 4971.29  241.87  4971.4  241.86
 4971.51  241.86  4976.5  241.71  4986.2  241.66  4995.4  237.74  4996.1  235.69
  5001.5   233.9  5003.5  237.58  5004.5  237.82  5016.9  241.56  5025.9   242.3
  5029.4  242.38 5029.59  242.39  5029.7  242.39 5029.81  242.39  5065.9  243.27
  5089.5  243.48  5103.8   243.6  5108.1  243.64    5150  243.78  5156.7  243.86
  5174.8  244.07  5175.2  243.53  5190.5  244.08  5203.5  244.15  5206.1  244.16
  5206.3  244.74  5209.2  245.07  5255.7  245.87    5265  246.03  5265.3   246.2
  5325.3   247.3  5365.3   247.6  5422.8  249.41  5435.3   249.8  5485.3   250.6
  5735.3   254.1  5785.3   253.5  5825.3   254.8  5935.3   255.4  5975.3   256.1
  5979.9   256.1
BR U #Mann= 4
  4134.2    .055  4986.2     .04  5016.9    .055  5103.8     .06
BR U Banks=4986.2,5016.9
BR D #Sta/Elev= 66
  4134.2   259.9    4160  259.19  4304.2   255.2  4334.2   254.7  4374.2   253.9
  4444.2   251.3  4574.2   248.6  4674.2   246.6  4694.2   245.7  4749.7  243.08
    4770  242.99    4775  242.97  4796.8  242.87  4826.3  242.45  4828.7  242.42
  4860.7  242.35  4906.2  242.23  4909.6  242.31    4932  242.85  4932.8  242.86
  4943.2  243.01  4957.1  242.29  4969.2  241.93 4971.29  241.87  4971.4  241.86
 4971.51  241.86  4976.5  241.71  4986.2  241.66  4995.4  237.74  4996.1  235.69
  5001.5   233.9  5003.5  237.58  5004.5  237.82  5016.9  241.56  5025.9   242.3
  5029.4  242.38 5029.59  242.39  5029.7  242.39 5029.81  242.39  5065.9  243.27
  5089.5  243.48  5103.8   243.6  5108.1  243.64    5150  243.78  5156.7  243.86
  5174.8  244.07  5175.2  243.53  5190.5  244.08  5203.5  244.15  5206.1  244.16
  5206.3  244.74  5209.2  245.07  5255.7  245.87    5265  246.03  5265.3   246.2
  5325.3   247.3  5365.3   247.6  5422.8  249.41  5435.3   249.8  5485.3   250.6
  5735.3   254.1  5785.3   253.5  5825.3   254.8  5935.3   255.4  5975.3   256.1
  5979.9   256.1
BR D #Mann= 4
  4134.2    .055  4986.2     .04  5016.9    .055  5103.8     .06
BR D Banks=4986.2,5016.9
BC Design=,, 0 ,, 0 ,,,,,,
BC HTab HWMax=259.98

Type RM Length L Ch R = 1 ,9150.9  ,245.3,233.2,233.2
BEGIN DESCRIPTION:
K166-01-00-S15_FAULKNER/MAIN-XS2
END DESCRIPTION:
XS GIS Cut Line= 4
      2943131.25     13944715.26      2942506.27      13944676.1
      2942002.01     13944643.46      2941290.19     13944710.93
#Sta/Elev= 30
  4134.2  259.98  4304.2  255.28  4374.2  253.98  4444.2  251.38  4674.2  246.68
  4749.7  243.16  4906.2  242.31  4943.2  243.09  4986.2  241.74  4995.4  237.82
  4996.1  235.77  5001.5  233.98  5003.5  237.66  5016.9  241.64  5025.9  242.38
  5065.9  243.35  5103.8  243.68  5174.8  244.15  5175.2  243.61  5206.1  244.24
  5206.3  244.82  5209.2  245.15  5325.3  247.38  5365.3  247.68  5435.3  249.88
  5485.3  250.68  5735.3  254.18  5785.3  253.58  5825.3  254.88  5979.9  256.18
#Mann= 5 ,-1 , 0
  4134.2    .055       0  4986.2     .04       0  5016.9    .055       0
  5103.8     .06       0  5979.9     .99       0
#XS Ineff= 2 , 0
       0 4979.53  241.81 5023.57       0  242.11
Permanent Ineff=
       F       F
Bank Sta=4986.2,5016.9
XS Rating Curve= 0
Exp/Cntr=.5,.3

Type RM Length L Ch R = 1 ,8917.7  ,61,57.5,56.8
BEGIN DESCRIPTION:
K166-01-00-S15_MILLSRD-XS2
END DESCRIPTION:
XS GIS Cut Line= 3
      2943103.14     13944474.31      2942083.79     13944415.89
      2941128.32     13944730.38
#Sta/Elev= 30
  4181.4  258.16  4371.4  253.26  4401.4  251.36    4704  243.18  4820.4   241.9
  4922.7   241.7  4930.4  241.04  4937.2  241.72  4975.2  242.37  4980.6   241.6
  4989.8  237.48  4990.3  234.25  5008.3  234.25 5008.41  236.54  5014.8  241.34
  5018.2   241.9  5056.4  241.13  5093.9  241.73  5232.4  248.46  5322.4  250.66
  5522.4  250.76  5542.4  251.56  5692.4  252.16  5732.4  250.96  5792.4  251.06
  5822.4  251.86  5952.4  251.06  6052.4  253.16  6142.4  252.86  6208.3  254.16
#Mann= 4 ,-1 , 0
  4181.4     .06       0  4975.2     .04       0  5018.2     .06       0
  6208.3     .99       0
#XS Ineff= 2 , 0
       0  4980.3  243.28  5018.4       0  243.28
Permanent Ineff=
       F       F
Bank Sta=4975.2,5018.2
XS Rating Curve= 0
Exp/Cntr=.5,.3

Type RM Length L Ch R = 2 ,8889.0  ,,,
BEGIN DESCRIPTION:
MILLS
Structure ID: K166-01-00-S14
Crossing pipe within culvert about 1.0' diameter-decreased culvert size to account for it-VRR
Tor of rail angled on one end VRR
Culvert diameter put back to surveyed size of 8'X8' and culvert n-value increase to 0.015. - JJA 3/14/03
END DESCRIPTION:
Bridge Culvert--1,0,-1,-1, 0
Deck Dist Width WeirC Skew NumUp NumDn MinLoCord MaxHiCord MaxSubmerge Is_Ogee
10,41,3,0, 53, 53, , , .95, 0, ,,,
  4181.4  4311.4  4371.4  4401.4  4621.4  4651.4  4662.8  4682.8    4704    4788
  4820.4  4896.6  4922.7  4930.4  4937.2  4958.9 4962.29  4962.4  4975.2  4980.6
  4989.8  4990.3  5008.3 5008.41  5010.2  5014.8  5018.2  5056.4  5074.4 5074.51
  5093.9  5102.1    5113  5131.4  5212.4  5232.4  5322.4  5332.8  5343.9  5512.4
  5522.4  5542.4  5632.4  5692.4  5732.4  5792.4  5822.4  5952.4  6052.4  6082.4
  6092.4  6142.4  6208.3
   258.1   254.4   253.2   251.3   245.1   244.7  244.37     244  243.41  242.39
   242.2  241.74  242.17  242.34   242.5     243  243.08  245.08  245.31  245.39
  245.38  245.38  245.37  245.37  245.37  245.36  245.36  245.33  245.32  243.32
  243.28  243.28  243.58  244.23  247.19  248.41  250.61   250.9     251   250.9
   250.7   251.5   251.4   252.1   250.9     251   251.8     251   253.1     253
   252.5   252.8   254.1
   258.1   254.4   253.2   251.3   245.1   244.7  244.36  243.76  243.12  242.17
  241.84  241.64  241.64  240.98  241.66   241.6  241.75  241.75  242.31  241.54
  237.42  234.19  234.19  236.48  237.39  241.28  241.84  241.07  241.36  241.36
  241.67  242.03  242.51  243.32   247.1   248.4   250.6  250.62  250.63   250.9
   250.7   251.5   251.4   252.1   250.9     251   251.8     251   253.1     253
   252.5   252.8   254.1
  4181.4  4311.4  4371.4  4401.4  4621.4  4651.4  4662.8  4682.8    4704    4788
  4820.4  4896.6  4922.7  4930.4  4937.2  4958.9 4962.29  4962.4  4975.2  4980.6
  4989.8  4990.3  5008.3 5008.41  5010.2  5014.8  5018.2  5056.4  5074.4 5074.51
  5093.9  5102.1    5113  5131.4  5212.4  5232.4  5322.4  5332.8  5343.9  5512.4
  5522.4  5542.4  5632.4  5692.4  5732.4  5792.4  5822.4  5952.4  6052.4  6082.4
  6092.4  6142.4  6208.3
   258.1   254.4   253.2   251.3   245.1   244.7  244.37     244  243.41  242.39
   242.2  241.74  242.17  242.34   242.5     243  243.08  245.08  245.31  245.39
  245.38  245.38  245.37  245.37  245.37  245.36  245.36  245.33  245.32  243.32
  243.28  243.28  243.58  244.23  247.19  248.41  250.61   250.9     251   250.9
   250.7   251.5   251.4   252.1   250.9     251   251.8     251   253.1     253
   252.5   252.8   254.1
   258.1   254.4   253.2   251.3   245.1   244.7  244.36  243.76  243.12  242.17
  241.84  241.64  241.64  240.98  241.66   241.6  241.75  241.75  242.31  241.54
  237.42  234.19  234.19  236.48  237.39  241.28  241.84  241.07  241.36  241.36
  241.67  242.03  242.51  243.32   247.1   248.4   250.6  250.62  250.63   250.9
   250.7   251.5   251.4   252.1   250.9     251   251.8     251   253.1     253
   252.5   252.8   254.1
BR Coef= 1 , 0 , 0 ,1.25, 0 ,,,.8,0,2,0,
WSPro=,,,, 1 ,,,, 0 ,,,, 0 ,,,,-1 ,-1 ,-1 , 0 , 0 , 0 , 0 , 0
Culvert=2,8,8,41,.015,.7,1,8,3,234.41,4994.3,234.19,4994.3,Culvert #1  , 0 ,10
Culvert Bottom n=.015
Culvert=2,8,8,41,.015,.7,1,8,3,234.76,5004.4,234.19,5004.4,Culvert #2  , 0 ,10
Culvert Bottom n=.015
BR U #Sta/Elev= 72
  4181.4   258.1  4311.4   254.4  4371.4   253.2  4401.4   251.3  4621.4   245.1
  4651.4   244.7  4662.8  244.36  4682.8  243.76    4704  243.12  4706.8  243.09
  4751.1  242.54    4788  242.17  4820.4  241.84  4896.6  241.64  4898.5  241.63
  4922.7  241.64  4924.9  241.45  4930.4  240.98  4937.2  241.66  4947.4  241.65
  4958.9   241.6 4962.29  241.75  4962.4  241.75 4962.51  241.76  4967.4  241.97
 4969.49  242.06  4969.6  242.07 4969.71  242.07  4975.2  242.31  4980.6  241.54
 4980.69   241.5  4980.8  241.45 4980.91   241.4  4989.8  237.42  4990.3  234.19
  5008.3  234.19 5008.41  236.48  5010.2  237.39  5014.8  241.28  5018.2  241.84
  5056.4  241.07 5074.29  241.36  5074.4  241.36 5074.51  241.36  5082.5  241.49
  5093.9  241.67  5102.1  242.03    5113  242.51  5131.4  243.32  5167.5  244.97
  5174.7   245.3  5205.4  246.78  5205.5  246.78  5212.4   247.1  5232.4   248.4
  5322.4   250.6  5332.8  250.62  5343.9  250.63  5512.4   250.9  5522.4   250.7
  5542.4   251.5  5632.4   251.4  5692.4   252.1  5732.4   250.9  5792.4     251
  5822.4   251.8  5952.4     251  6052.4   253.1  6082.4     253  6092.4   252.5
  6142.4   252.8  6208.3   254.1
BR U #Mann= 3
  4181.4     .06  4975.2     .04  5018.2     .06
BR U Banks=4975.2,5018.2
BR D #Sta/Elev= 72
  4181.4   258.1  4311.4   254.4  4371.4   253.2  4401.4   251.3  4621.4   245.1
  4651.4   244.7  4662.8  244.36  4682.8  243.76    4704  243.12  4706.8  243.09
  4751.1  242.54    4788  242.17  4820.4  241.84  4896.6  241.64  4898.5  241.63
  4922.7  241.64  4924.9  241.45  4930.4  240.98  4937.2  241.66  4947.4  241.65
  4958.9   241.6 4962.29  241.75  4962.4  241.75 4962.51  241.76  4967.4  241.97
 4969.49  242.06  4969.6  242.07 4969.71  242.07  4975.2  242.31  4980.6  241.54
 4980.69   241.5  4980.8  241.45 4980.91   241.4  4989.8  237.42  4990.3  234.19
  5008.3  234.19 5008.41  236.48  5010.2  237.39  5014.8  241.28  5018.2  241.84
  5056.4  241.07 5074.29  241.36  5074.4  241.36 5074.51  241.36  5082.5  241.49
  5093.9  241.67  5102.1  242.03    5113  242.51  5131.4  243.32  5167.5  244.97
  5174.7   245.3  5205.4  246.78  5205.5  246.78  5212.4   247.1  5232.4   248.4
  5322.4   250.6  5332.8  250.62  5343.9  250.63  5512.4   250.9  5522.4   250.7
  5542.4   251.5  5632.4   251.4  5692.4   252.1  5732.4   250.9  5792.4     251
  5822.4   251.8  5952.4     251  6052.4   253.1  6082.4     253  6092.4   252.5
  6142.4   252.8  6208.3   254.1
BR D #Mann= 3
  4181.4     .06  4975.2     .04  5018.2     .06
BR D Banks=4975.2,5018.2
BC Design=,, 0 ,, 0 ,,,,,,
BC HTab HWMax=258.16

Type RM Length L Ch R = 1 ,8860.2  ,69.7,64.1,60.6
BEGIN DESCRIPTION:
K166-01-00-S15_MILLSRD-XS2
END DESCRIPTION:
XS GIS Cut Line= 3
      2943104.53     13944417.52      2942084.23     13944359.05
      2941127.86     13944673.84
#Sta/Elev= 30
  4181.4  258.45  4371.4  253.55  4401.4  251.65    4704  243.47  4820.4  242.19
  4922.7  241.99  4930.4  241.33  4937.2  242.01  4975.2  242.66  4980.6  241.89
  4989.8  237.77  4990.3  234.54  5008.3  234.54 5008.41  236.83  5014.8  241.63
  5018.2  242.19  5056.4  241.42  5093.9  242.02  5232.4  248.75  5322.4  250.95
  5522.4  251.05  5542.4  251.85  5692.4  252.45  5732.4  251.25  5792.4  251.35
  5822.4  252.15  5952.4  251.35  6052.4  253.45  6142.4  253.15  6208.3  254.45
#Mann= 4 ,-1 , 0
  4181.4     .06       0  4975.2     .04       0  5018.2     .06       0
  6208.3     .99       0
#XS Ineff= 2 , 0
       0  4980.3  241.74  5018.4       0     242
Permanent Ineff=
       F       F
Bank Sta=4975.2,5018.2
XS Rating Curve= 0
Exp/Cntr=.5,.3

Type RM Length L Ch R = 1 ,8796.1  ,26.7,25.9,26
BEGIN DESCRIPTION:
K166-01-00-S14A_WOODBRIDGE-XS3
END DESCRIPTION:
XS GIS Cut Line= 4
      2943100.09     13944342.72      2942523.03     13944316.67
      2942006.47     13944299.69      2941008.08     13944702.97
#Sta/Elev= 30
    4171  257.65    4341  252.95    4371  250.75    4511  247.35    4551  247.45
    4621  245.05    4731  244.35    4746  243.25  4788.6  242.69  4926.6   241.9
  4982.7  242.86  4995.7  236.95  4999.9  236.74  5004.6  237.66  5015.2  237.98
  5027.2  244.36  5043.1  246.16  5144.8  245.85  5264.4  246.72  5265.5  247.35
  5375.5  249.95  5565.5  250.65  5775.5  248.75  5805.5  249.35  5825.5  248.25
  5965.5  249.35  5985.5  250.15  6165.5  250.05  6225.5  252.65  6342.2  252.95
#Mann= 4 ,-1 , 0
    4171     .06       0  4982.7     .04       0  5027.2     .06       0
  6342.2     .99       0
#XS Ineff= 2 , 0
       0  4972.7  243.58  5037.2       0   245.6
Permanent Ineff=
       F       F
Bank Sta=4982.7,5027.2
XS Rating Curve= 0
Exp/Cntr=.5,.3

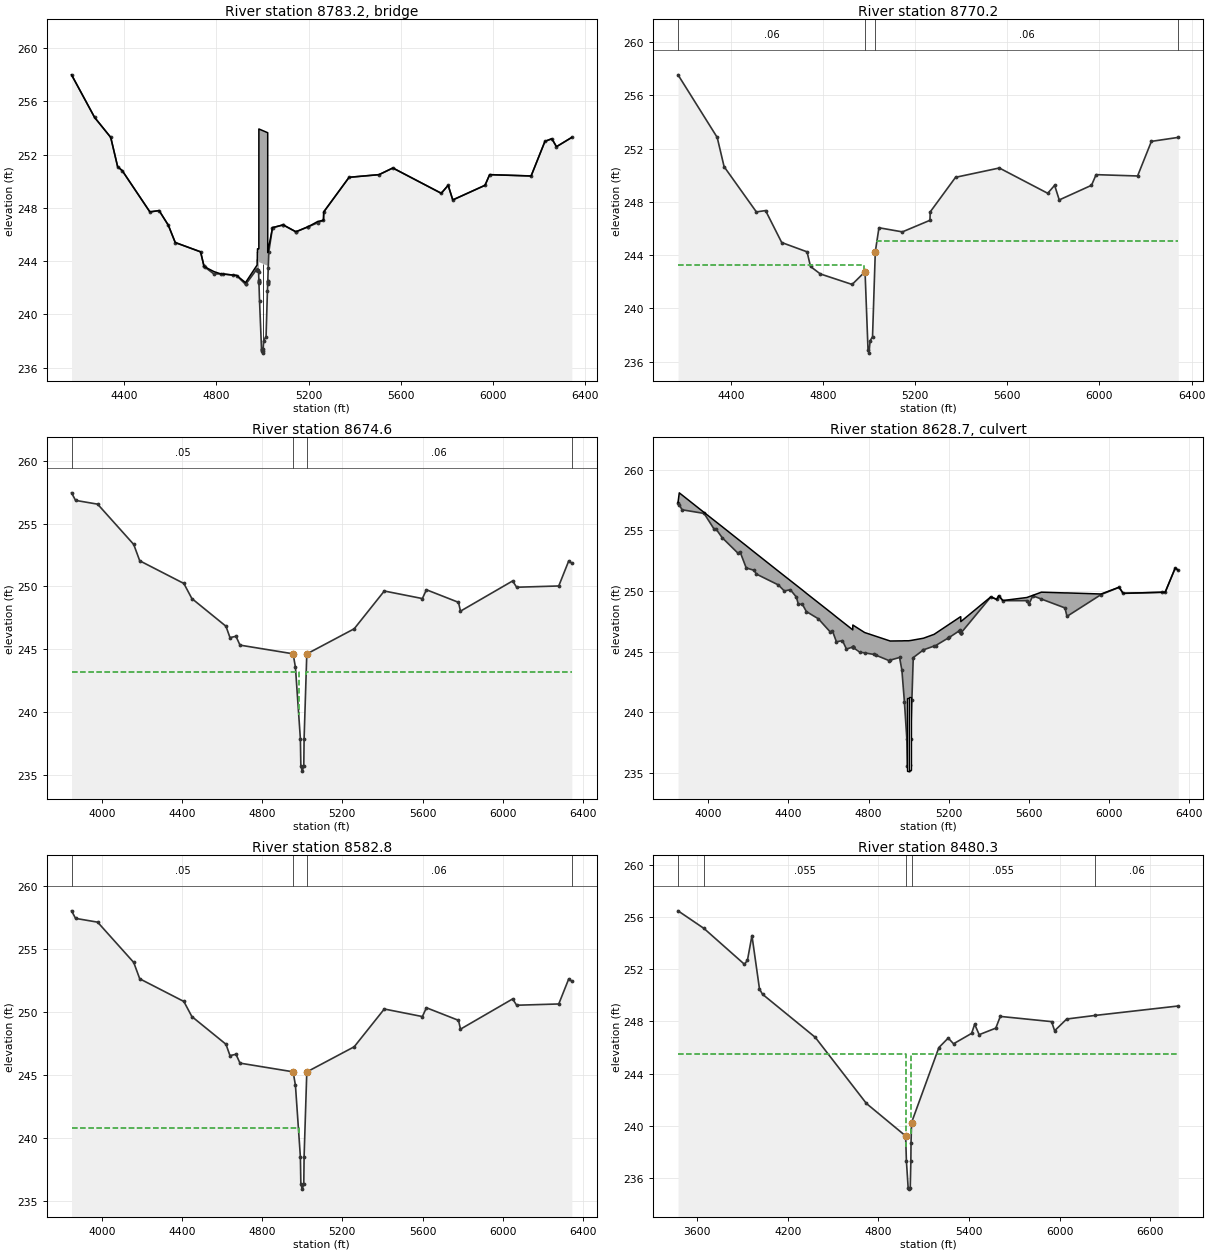
Type RM Length L Ch R = 3 ,8783.2  ,,,
BEGIN DESCRIPTION:
WOOD BRIDGE 84' DS MILLS
Structure ID: K166-01-00-S14A
Thin pier in center of channel-added per photo 11/14/2 VRR
END DESCRIPTION:
Bridge Culvert--1,0,-1,-1, 0
Deck Dist Width WeirC Skew NumUp NumDn MinLoCord MaxHiCord MaxSubmerge Is_Ogee
10,6,2.6,0, 52, 52, , , .95, 0, ,,,
    4171    4271    4341    4371    4391    4511    4551    4591    4621    4731
    4746  4788.6  4817.6  4887.3    4926  4974.1  4976.4  4976.5  4977.1  4977.4
  4977.8  4978.1  4982.7 4983.87 4983.98 4984.21  4984.3 5022.37 5022.48 5022.59
  5022.7  5027.2  5043.1  5089.2  5144.8    5199  5240.2  5264.4  5265.5  5375.5
  5505.5  5565.5  5775.5  5805.5  5825.5  5965.5  5985.5  6165.5  6225.5  6255.5
  6275.5  6342.2
     258   254.8   253.3   251.1   250.8   247.7   247.8   246.7   245.4   244.7
   243.6  243.22  243.05  242.93  242.39  243.65  243.71  244.06  244.06  244.65
  244.65  244.93  244.93  244.93  253.93  253.93  253.93  253.65  244.65  244.66
  244.67   245.1  246.52  246.73  246.21   246.6  246.99  247.07   247.7   250.3
   250.5     251   249.1   249.7   248.6   249.7   250.5   250.4     253   253.2
   252.6   253.3
     258   254.8   253.3   251.1   250.8   247.7   247.8   246.7   245.4   244.7
   243.6  243.04  243.04  242.92  242.26  243.37  243.33  243.33  243.31  243.31
   243.3   243.3  243.21  242.59  242.53  242.41  243.93  243.65  243.65  243.66
  242.53  244.71  246.51  246.72   246.2  246.59  246.89  247.07   247.7   250.3
   250.5     251   249.1   249.7   248.6   249.7   250.5   250.4     253   253.2
   252.6   253.3
    4171    4271    4341    4371    4391    4511    4551    4591    4621    4731
    4746  4788.6  4817.6  4887.3    4926  4974.1  4976.4  4976.5  4977.1  4977.4
  4977.8  4978.1  4982.7 4983.87 4983.98 4984.21  4984.3 5022.37 5022.48 5022.59
  5022.7  5027.2  5043.1  5089.2  5144.8    5199  5240.2  5264.4  5265.5  5375.5
  5505.5  5565.5  5775.5  5805.5  5825.5  5965.5  5985.5  6165.5  6225.5  6255.5
  6275.5  6342.2
     258   254.8   253.3   251.1   250.8   247.7   247.8   246.7   245.4   244.7
   243.6  243.22  243.05  242.93  242.39  243.65  243.71  244.06  244.06  244.65
  244.65  244.93  244.93  244.93  253.93  253.93  253.93  253.65  244.65  244.66
  244.67   245.1  246.52  246.73  246.21   246.6  246.99  247.07   247.7   250.3
   250.5     251   249.1   249.7   248.6   249.7   250.5   250.4     253   253.2
   252.6   253.3
     258   254.8   253.3   251.1   250.8   247.7   247.8   246.7   245.4   244.7
   243.6  243.04  243.04  242.92  242.26  243.37  243.33  243.33  243.31  243.31
   243.3   243.3  243.21  242.59  242.53  242.41  243.93  243.65  243.65  243.66
  242.53  244.71  246.51  246.72   246.2  246.59  246.89  247.07   247.7   250.3
   250.5     251   249.1   249.7   248.6   249.7   250.5   250.4     253   253.2
   252.6   253.3
Pier Skew, UpSta & Num, DnSta & Num=  ,5000, 2 ,5000, 2 , 0 , 0 , 0 ,,
      .5      .5
  236.11  244.81
      .5      .5
   235.8   244.5
BR Coef= 1 , 1 , 1 ,1.25, 0 ,,,.8,0,2,0,
WSPro=,,,, 1 ,,,, 0 ,,,, 0 ,,,,-1 ,-1 ,-1 , 0 , 0 , 0 , 0 , 0
BR U #Sta/Elev= 74
    4171     258    4271   254.8    4341   253.3    4371   251.1    4391   250.8
    4511   247.7    4551   247.8    4591   246.7    4621   245.4    4731   244.7
  4745.8  243.63    4746   243.6  4750.5  243.54  4788.6  243.04  4817.6  243.04
  4829.2  243.04  4872.2  242.95  4887.3  242.92    4926  242.26  4926.6  242.25
  4974.1  243.37  4976.4  243.33  4976.5  243.33  4977.1  243.31  4977.4  243.31
  4977.8   243.3  4978.1   243.3  4982.7  243.21 4983.87  242.59 4983.98  242.53
 4984.09  242.47 4984.21  242.41  4984.3  242.36  4986.8  241.04  4995.7   237.3
  4997.4  237.41  4998.7  237.27  4999.9  237.09  5001.7  237.23  5002.5  237.38
  5004.6  238.01  5015.2  238.33  5021.1  241.76 5022.26  242.32 5022.37  242.37
 5022.48  242.43 5022.59  242.48  5022.7  242.53  5024.6  243.45  5027.2  244.71
  5043.1  246.51    5044  246.51  5088.9  246.72  5089.2  246.72  5143.8  246.21
  5144.8   246.2  5198.7  246.59    5199  246.59  5240.2  246.89  5264.4  247.07
  5265.5   247.7  5375.5   250.3  5505.5   250.5  5565.5     251  5775.5   249.1
  5805.5   249.7  5825.5   248.6  5965.5   249.7  5985.5   250.5  6165.5   250.4
  6225.5     253  6255.5   253.2  6275.5   252.6  6342.2   253.3
BR U #Mann= 3
    4171     .06  4982.7     .04  5027.2     .06
BR U Banks=4982.7,5027.2
BR D #Sta/Elev= 74
    4171     258    4271   254.8    4341   253.3    4371   251.1    4391   250.8
    4511   247.7    4551   247.8    4591   246.7    4621   245.4    4731   244.7
  4745.8  243.63    4746   243.6  4750.5  243.54  4788.6  243.04  4817.6  243.04
  4829.2  243.04  4872.2  242.95  4887.3  242.92    4926  242.26  4926.6  242.25
  4974.1  243.37  4976.4  243.33  4976.5  243.33  4977.1  243.31  4977.4  243.31
  4977.8   243.3  4978.1   243.3  4982.7  243.21 4983.87  242.59 4983.98  242.53
 4984.09  242.47 4984.21  242.41  4984.3  242.36  4986.8  241.04  4995.7   237.3
  4997.4  237.41  4998.7  237.27  4999.9  237.09  5001.7  237.23  5002.5  237.38
  5004.6  238.01  5015.2  238.33  5021.1  241.76 5022.26  242.32 5022.37  242.37
 5022.48  242.43 5022.59  242.48  5022.7  242.53  5024.6  243.45  5027.2  244.71
  5043.1  246.51    5044  246.51  5088.9  246.72  5089.2  246.72  5143.8  246.21
  5144.8   246.2  5198.7  246.59    5199  246.59  5240.2  246.89  5264.4  247.07
  5265.5   247.7  5375.5   250.3  5505.5   250.5  5565.5     251  5775.5   249.1
  5805.5   249.7  5825.5   248.6  5965.5   249.7  5985.5   250.5  6165.5   250.4
  6225.5     253  6255.5   253.2  6275.5   252.6  6342.2   253.3
BR D #Mann= 3
    4171     .06  4982.7     .04  5027.2     .06
BR D Banks=4982.7,5027.2
BC Design=,, 0 ,, 0 ,,,,,,
BC HTab HWMax=257.65

Type RM Length L Ch R = 1 ,8770.2  ,136.9,95.6,62
BEGIN DESCRIPTION:
K166-01-00-S14A_WOODBRIDGE-XS2
END DESCRIPTION:
XS GIS Cut Line= 4
      2943094.95     13944317.48      2942517.86     13944291.43
      2942000.22     13944274.42      2941000.84     13944678.08
#Sta/Elev= 30
    4171  257.55    4341  252.85    4371  250.65    4511  247.25    4551  247.35
    4621  244.95    4731  244.25    4746  243.15  4788.6  242.59  4926.6   241.8
  4982.7  242.76  4995.7  236.85  4999.9  236.64  5004.6  237.56  5015.2  237.88
  5027.2  244.26  5043.1  246.06  5144.8  245.75  5264.4  246.62  5265.5  247.25
  5375.5  249.85  5565.5  250.55  5775.5  248.65  5805.5  249.25  5825.5  248.15
  5965.5  249.25  5985.5  250.05  6165.5  249.95  6225.5  252.55  6342.2  252.85
#Mann= 4 ,-1 , 0
    4171     .06       0  4982.7     .04       0  5027.2     .06       0
  6342.2     .99       0
#XS Ineff= 2 , 0
       0 4976.03  243.26 5033.87       0   245.1
Permanent Ineff=
       F       F
Bank Sta=4982.7,5027.2
XS Rating Curve= 0
Exp/Cntr=.5,.3

Type RM Length L Ch R = 1 ,8674.6  ,119.7,91.8,90.3
BEGIN DESCRIPTION:
K166-01-00-S12_BUS290EB-XS3
END DESCRIPTION:
XS GIS Cut Line= 4
      2943355.04      13943915.7       2942516.3     13944119.84
      2941987.19     13944256.01      2940980.91     13944662.22
#Sta/Elev= 30
  3849.6  257.44  3869.6  256.84  3979.6  256.54  4159.6  253.34  4189.6  252.04
  4409.6  250.24  4449.6  249.04  4619.6  246.84  4639.6  245.94  4669.6  246.04
  4689.6  245.34  4954.5  244.65  4966.1  243.58  4990.7  237.91  4993.1  235.73
  5000.1  235.33  5007.7  235.74  5009.3  237.91  5022.7  244.64  5259.2  246.64
  5409.2  249.64  5599.2  249.04  5619.2  249.74  5779.2  248.74  5789.2  248.04
  6049.2  250.44  6069.2  249.94  6279.2  250.04  6329.2  252.04  6344.4  251.84
#Mann= 4 ,-1 , 0
  3849.6     .05       0  4954.5     .04       0  5022.7     .06       0
  6344.4     .99       0
#XS Ineff= 2 , 0
       0 4982.44   243.2 5019.41       0   243.2
Permanent Ineff=
       F       F
Bank Sta=4954.5,5022.7
XS Rating Curve= 0
Exp/Cntr=.5,.3

Type RM Length L Ch R = 2 ,8628.7  ,,,
BEGIN DESCRIPTION:
BUSINESS 290 EB;Rail only over short section 11/14/2 VRR
Structure ID: K166-01-00-S12
END DESCRIPTION:
Bridge Culvert--1,0,-1,-1, 0
Deck Dist Width WeirC Skew NumUp NumDn MinLoCord MaxHiCord MaxSubmerge Is_Ogee
10,74,3,0, 60, 60, , , .95, 0, ,,,
  3849.6  3855.8  3869.6  3979.6  4029.6  4039.6  4069.6  4149.6  4159.6  4189.6
  4229.6  4239.6  4349.6  4379.6  4409.6  4439.6  4449.6  4469.6  4489.6  4549.6
  4609.6  4619.6  4639.6  4669.6  4689.6    4721 4721.31  4780.3  4907.5  4954.5
  4966.1  4978.5  4990.7  4993.1  5000.1  5007.7  5009.3  5022.7  5073.5  5126.6
    5258  5259.2  5259.7 5259.81  5409.2  5439.2  5449.2  5469.2  5589.2  5599.2
  5619.2  5661.9  5779.2  5789.2  5959.2  6049.2  6069.2  6279.2  6329.2  6344.4
   257.3   258.1  257.92  256.48  255.83   255.7  255.31  254.26  254.13  253.74
  253.21  253.08  251.64  251.25  250.86  250.47  250.34  250.08  249.81  249.03
  248.25  248.12  247.85  247.46   247.2  246.79  247.19  246.57  245.87  245.88
  245.88  245.89  245.89  245.89  245.89  245.91  245.91  245.95   246.1  246.42
  247.87  247.87  247.87  247.47  249.51  249.31  249.61  249.21  249.46  249.52
  249.64   249.9  249.84  249.84  249.75  250.31  249.81   249.9   251.9   251.7
   257.3  257.11   256.7   256.4   255.1   255.1   254.4   253.1   253.2   251.9
   251.7   251.4   250.5     250   250.1   249.5   248.9   248.9   248.3   247.7
   246.6   246.7   245.8   245.9   245.2  245.36  245.35  244.89  244.29  244.51
  243.44  240.86  237.77  235.59  235.19   235.6  237.77   244.5  245.14  245.45
  246.77   246.5  246.51  246.51   249.5   249.3   249.6   249.2   249.2   248.9
   249.6  249.33   248.6   247.9   249.7   250.3   249.8   249.9   251.9   251.7
  3849.6  3855.8  3869.6  3979.6  4029.6  4039.6  4069.6  4149.6  4159.6  4189.6
  4229.6  4239.6  4349.6  4379.6  4409.6  4439.6  4449.6  4469.6  4489.6  4549.6
  4609.6  4619.6  4639.6  4669.6  4689.6    4721 4721.31  4780.3  4907.5  4954.5
  4966.1  4978.5  4990.7  4993.1  5000.1  5007.7  5009.3  5022.7  5073.5  5126.6
    5258  5259.2  5259.7 5259.81  5409.2  5439.2  5449.2  5469.2  5589.2  5599.2
  5619.2  5661.9  5779.2  5789.2  5959.2  6049.2  6069.2  6279.2  6329.2  6344.4
   257.3   258.1  257.92  256.48  255.83   255.7  255.31  254.26  254.13  253.74
  253.21  253.08  251.64  251.25  250.86  250.47  250.34  250.08  249.81  249.03
  248.25  248.12  247.85  247.46   247.2  246.79  247.19  246.57  245.87  245.88
  245.88  245.89  245.89  245.89  245.89  245.91  245.91  245.95   246.1  246.42
  247.87  247.87  247.87  247.47  249.51  249.31  249.61  249.21  249.46  249.52
  249.64   249.9  249.84  249.84  249.75  250.31  249.81   249.9   251.9   251.7
   257.3  257.11   256.7   256.4   255.1   255.1   254.4   253.1   253.2   251.9
   251.7   251.4   250.5     250   250.1   249.5   248.9   248.9   248.3   247.7
   246.6   246.7   245.8   245.9   245.2  245.36  245.35  244.89  244.29  244.51
  243.44  240.86  237.77  235.59  235.19   235.6  237.77   244.5  245.14  245.45
  246.77   246.5  246.51  246.51   249.5   249.3   249.6   249.2   249.2   248.9
   249.6  249.33   248.6   247.9   249.7   250.3   249.8   249.9   251.9   251.7
BR Coef= 1 , 0 , 0 ,1.25, 0 ,,,.8,0,2,0,
WSPro=,,,, 1 ,,,, 0 ,,,, 0 ,,,,-1 ,-1 ,-1 , 0 , 0 , 0 , 0 , 0
Culvert=2,6,8.3,74,.013,.7,1,8,3,235.13,4996.6,234.93,4996.6,Culvert #1  , 0 ,10
Culvert Bottom n=.013
Culvert=2,6,8.2,74,.013,.7,1,8,3,235.21,5005.3,234.91,5005.3,Culvert #2  , 0 ,10
Culvert Bottom n=.013
BR U #Sta/Elev= 76
  3849.6   257.3  3855.8  257.11  3869.6   256.7  3979.6   256.4  4029.6   255.1
  4039.6   255.1  4069.6   254.4  4149.6   253.1  4159.6   253.2  4189.6   251.9
  4229.6   251.7  4239.6   251.4  4349.6   250.5  4379.6     250  4409.6   250.1
  4439.6   249.5  4449.6   248.9  4469.6   248.9  4489.6   248.3  4549.6   247.7
  4609.6   246.6  4619.6   246.7  4639.6   245.8  4669.6   245.9  4689.6   245.2
  4719.9  245.37    4721  245.36 4721.09  245.36  4721.2  245.36 4721.31  245.35
  4756.6  244.95  4780.3  244.89  4826.8  244.76  4837.7  244.69  4901.1  244.26
  4907.5  244.29  4954.5  244.51  4966.1  243.44  4978.5  240.86  4990.7  237.77
  4993.1  235.59    5000   235.2  5000.1  235.19  5007.7   235.6  5009.3  237.77
  5015.9  241.03  5022.7   244.5  5070.7   245.1  5073.5  245.14  5126.6  245.45
    5134  245.49  5194.4  246.09  5202.9  246.17  5253.1  246.72    5258  246.77
  5259.2   246.5 5259.59  246.51  5259.7  246.51 5259.81  246.51  5409.2   249.5
  5439.2   249.3  5449.2   249.6  5469.2   249.2  5589.2   249.2  5599.2   248.9
  5619.2   249.6  5661.9  249.33  5779.2   248.6  5789.2   247.9  5959.2   249.7
  6049.2   250.3  6069.2   249.8    6261  249.89  6279.2   249.9  6329.2   251.9
  6344.4   251.7
BR U #Mann= 3
  3849.6     .05  4954.5     .04  5022.7     .06
BR U Banks=4954.5,5022.7
BR D #Sta/Elev= 76
  3849.6   257.3  3855.8  257.11  3869.6   256.7  3979.6   256.4  4029.6   255.1
  4039.6   255.1  4069.6   254.4  4149.6   253.1  4159.6   253.2  4189.6   251.9
  4229.6   251.7  4239.6   251.4  4349.6   250.5  4379.6     250  4409.6   250.1
  4439.6   249.5  4449.6   248.9  4469.6   248.9  4489.6   248.3  4549.6   247.7
  4609.6   246.6  4619.6   246.7  4639.6   245.8  4669.6   245.9  4689.6   245.2
  4719.9  245.37    4721  245.36 4721.09  245.36  4721.2  245.36 4721.31  245.35
  4756.6  244.95  4780.3  244.89  4826.8  244.76  4837.7  244.69  4901.1  244.26
  4907.5  244.29  4954.5  244.51  4966.1  243.44  4978.5  240.86  4990.7  237.77
  4993.1  235.59    5000   235.2  5000.1  235.19  5007.7   235.6  5009.3  237.77
  5015.9  241.03  5022.7   244.5  5070.7   245.1  5073.5  245.14  5126.6  245.45
    5134  245.49  5194.4  246.09  5202.9  246.17  5253.1  246.72    5258  246.77
  5259.2   246.5 5259.59  246.51  5259.7  246.51 5259.81  246.51  5409.2   249.5
  5439.2   249.3  5449.2   249.6  5469.2   249.2  5589.2   249.2  5599.2   248.9
  5619.2   249.6  5661.9  249.33  5779.2   248.6  5789.2   247.9  5959.2   249.7
  6049.2   250.3  6069.2   249.8    6261  249.89  6279.2   249.9  6329.2   251.9
  6344.4   251.7
BR D #Mann= 3
  3849.6     .05  4954.5     .04  5022.7     .06
BR D Banks=4954.5,5022.7
BC Design=,, 0 ,, 0 ,,,,,,
BC HTab HWMax=257.44

Type RM Length L Ch R = 1 ,8582.8  ,90.6,102.5,63
BEGIN DESCRIPTION:
K166-01-00-S12_BUS290EB-XS2
END DESCRIPTION:
XS GIS Cut Line= 4
      2943321.65      13943831.1      2942482.87     13944035.25
      2941953.42     13944171.52      2940946.83     13944577.85
#Sta/Elev= 30
  3849.6  258.04  3869.6  257.44  3979.6  257.14  4159.6  253.94  4189.6  252.64
  4409.6  250.84  4449.6  249.64  4619.6  247.44  4639.6  246.54  4669.6  246.64
  4689.6  245.94  4954.5  245.25  4966.1  244.18  4990.7  238.51  4993.1  236.33
  5000.1  235.93  5007.7  236.34  5009.3  238.51  5022.7  245.24  5259.2  247.24
  5409.2  250.24  5599.2  249.64  5619.2  250.34  5779.2  249.34  5789.2  248.64
  6049.2  251.04  6069.2  250.54  6279.2  250.64  6329.2  252.64  6344.4  252.44
#Mann= 4 ,-1 , 0
  3849.6     .05       0  4954.5     .08       0  5022.7     .06       0
  6344.4     .99       0
#XS Ineff= 2 , 0
       0 4982.44   240.8 5019.41       0   240.8
Permanent Ineff=
       F       F
Bank Sta=4954.5,5022.7
XS Rating Curve= 0
Exp/Cntr=.5,.3

Type RM Length L Ch R = 1 ,8480.3  ,70.8,51.4,49.6
BEGIN DESCRIPTION:
K166-01-00-S11_UPRR-XS3
END DESCRIPTION:
XS GIS Cut Line= 4
      2943589.17     13943663.65      2942716.77     13943919.73
      2941825.61      13944135.2      2940394.73     13944549.07
#Sta/Elev= 30
  3471.6  256.48  3643.5  255.13  3911.6  252.38  3931.6  252.68  3961.6  254.58
  4011.6  250.48  4031.6  250.08  4380.8  246.78  4720.3   241.7  4980.1  239.21
  4985.2   237.3  4996.9  235.21  5004.3  235.13  5010.6   235.2  5014.8   237.3
  5015.9  238.69  5019.5  240.24  5200.4  245.99  5262.4  246.72  5297.6  246.28
  5417.6  247.08  5437.6  247.78  5467.6  246.98  5577.6  247.48  5607.5  248.38
  5947.6  247.98  5967.6  247.28  6047.6  248.18  6232.5  248.45  6787.2  249.18
#Mann= 5 ,-1 , 0
  3471.6     .99       0  3643.5    .055       0  4980.1     .08       0
  5019.5    .055       0  6232.5     .06       0
#XS Ineff= 2 , 0
       0 4982.41   245.5 5017.49       0   245.5
Permanent Ineff=
       F       F
Bank Sta=4980.1,5019.5
XS Rating Curve= 0
Exp/Cntr=.5,.3