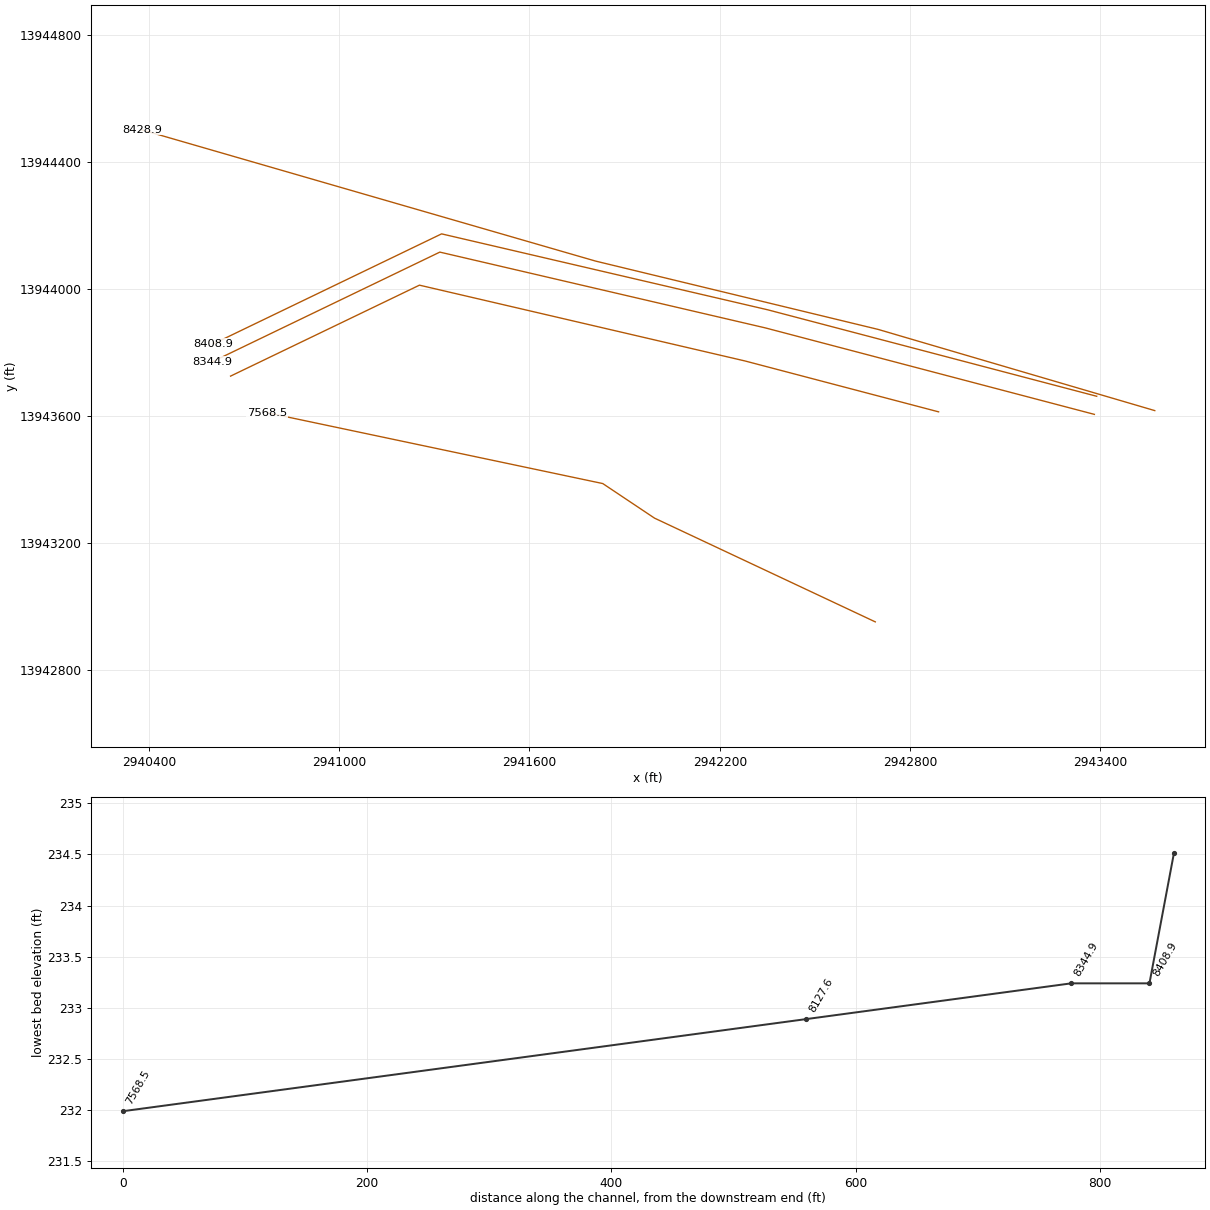
HEC-RAS study K166-01-00.prj: K166-01-00

--- K166-01-00.g01 (geometry) --- (continued)

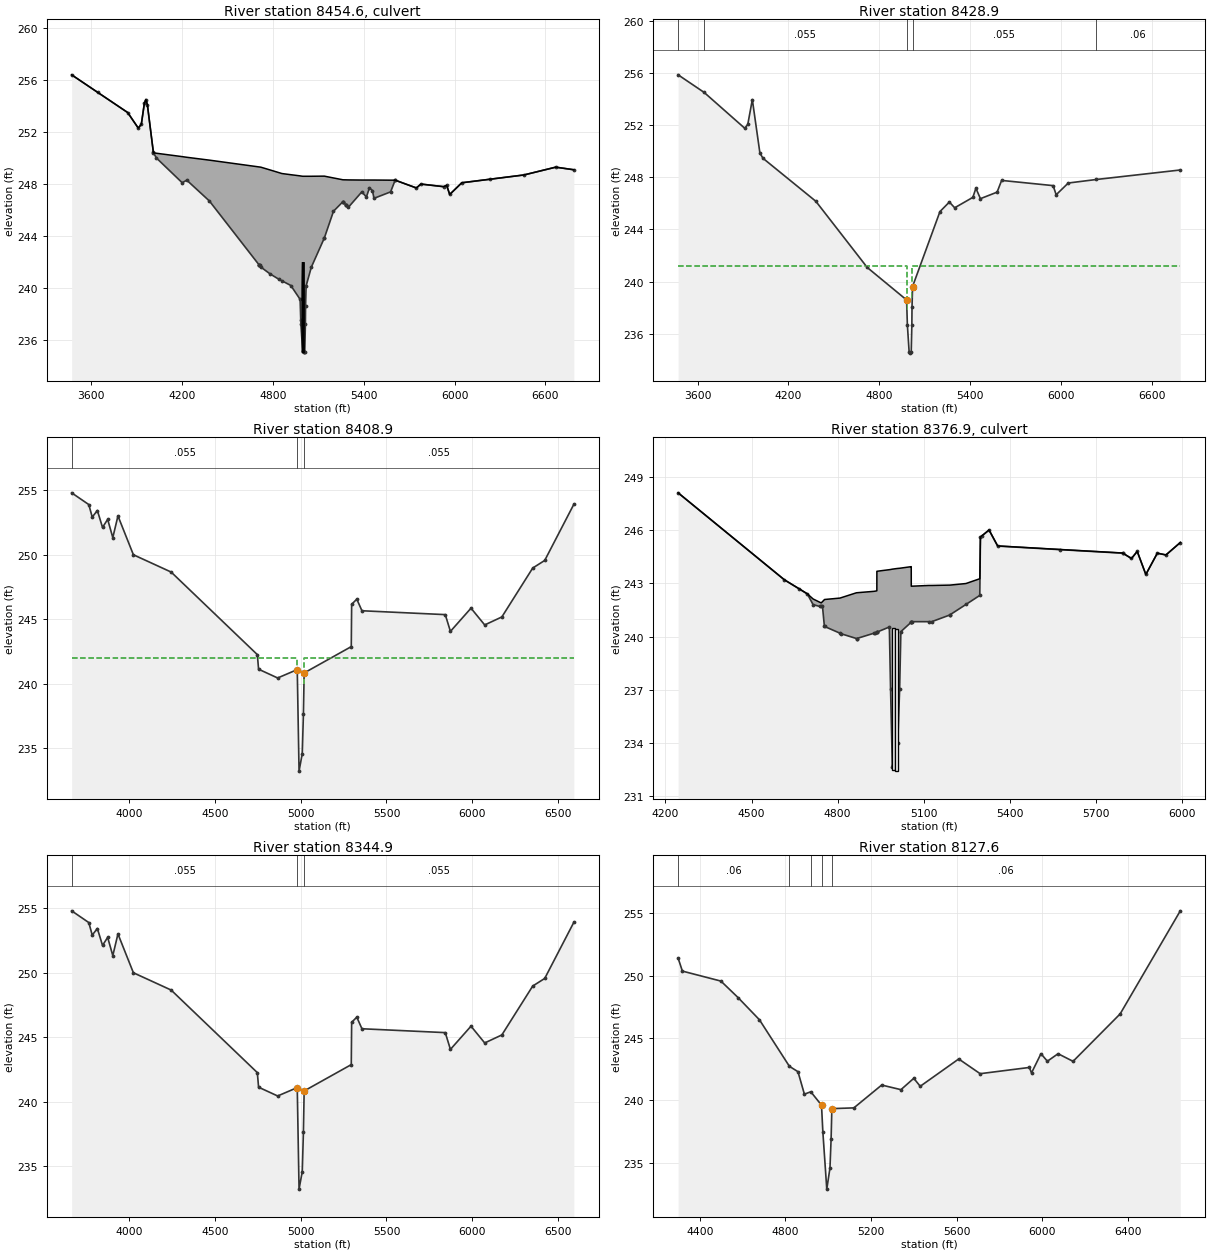
Type RM Length L Ch R = 2 ,8454.6  ,,,
BEGIN DESCRIPTION:
UNION PACIFIC RR; Estimated culvert size and elev- CHANGE ONCE SURVEY COMES IN- VRR
Structure ID: K166-01-00-S11
Right side spills outside of waterhed-all low points to right 11/15/2 VRR
END DESCRIPTION:
Bridge Culvert--1,0,-1,-1, 0
Deck Dist Width WeirC Skew NumUp NumDn MinLoCord MaxHiCord MaxSubmerge Is_Ogee
10,34,2.6,0, 46, 46, , , .95, 0, ,,,
  3471.6  3841.6  3911.6  3931.6  3951.6  3961.6  3971.6  4011.6  4031.6  4201.6
  4231.6  4380.8  4720.3  4780.5  4859.8  4918.6  4980.1  4984.2  4985.2  4996.9
  5004.3  5010.6  5014.8  5015.9  5019.5  5054.1  5139.6  5200.4  5262.4  5297.6
  5387.6  5417.6  5437.6  5457.6  5467.6  5577.6  5607.5  5747.6  5777.6  5927.6
  5947.6  5967.6  6047.6  6457.6  6667.6  6787.2
   256.4   253.5   252.3   252.6   254.2   254.5   254.1   250.4  250.37  250.11
  250.06  249.84   249.3  249.09  248.81  248.72  248.63  248.62  248.62   248.6
   248.6   248.6   248.6   248.6   248.6   248.6  248.61  248.47  248.33  248.32
  248.31  248.31  248.31  248.31  248.31   248.3   248.3   247.7     248   247.8
   247.9   247.2   248.1   248.7   249.3   249.1
   256.4   253.5   252.3   252.6   254.2   254.5   254.1   250.4     250   248.1
   248.3   246.7  241.62   241.1  240.56   240.2  239.13  237.53  237.22  235.13
  235.05  235.12  237.22  238.61  240.16  241.61  243.84  245.91  246.64   246.2
   247.4     247   247.7   247.5   246.9   247.4   248.3   247.7     248   247.8
   247.9   247.2   248.1   248.7   249.3   249.1
  3471.6  3841.6  3911.6  3931.6  3951.6  3961.6  3971.6  4011.6  4031.6  4201.6
  4231.6  4380.8  4720.3  4780.5  4859.8  4918.6  4980.1  4984.2  4985.2  4996.9
  5004.3  5010.6  5014.8  5015.9  5019.5  5054.1  5139.6  5200.4  5262.4  5297.6
  5387.6  5417.6  5437.6  5457.6  5467.6  5577.6  5607.5  5747.6  5777.6  5927.6
  5947.6  5967.6  6047.6  6457.6  6667.6  6787.2
   256.4   253.5   252.3   252.6   254.2   254.5   254.1   250.4  250.37  250.11
  250.06  249.84   249.3  249.09  248.81  248.72  248.63  248.62  248.62   248.6
   248.6   248.6   248.6   248.6   248.6   248.6  248.61  248.47  248.33  248.32
  248.31  248.31  248.31  248.31  248.31   248.3   248.3   247.7     248   247.8
   247.9   247.2   248.1   248.7   249.3   249.1
   256.4   253.5   252.3   252.6   254.2   254.5   254.1   250.4     250   248.1
   248.3   246.7  241.62   241.1  240.56   240.2  239.13  237.53  237.22  235.13
  235.05  235.12  237.22  238.61  240.16  241.61  243.84  245.91  246.64   246.2
   247.4     247   247.7   247.5   246.9   247.4   248.3   247.7     248   247.8
   247.9   247.2   248.1   248.7   249.3   249.1
BR Coef= 1 , 0 , 0 ,1.25, 0 ,,,.8,0,2,0,
WSPro=,,,, 1 ,,,, 0 ,,,, 0 ,,,,-1 ,-1 ,-1 , 0 , 0 , 0 , 0 , 0
Culvert=1,7,,34,.015,.5,1,2,1,235,4996,235,4996,Culvert #1  , 0 ,10
Culvert Bottom n=.015
Culvert=1,7,,34,.015,.5,1,2,1,235,5004,235,5004,Culvert #2  , 0 ,10
Culvert Bottom n=.015
BR U #Sta/Elev= 63
  3471.6   256.4  3643.5  255.05  3841.6   253.5  3911.6   252.3  3931.6   252.6
  3951.6   254.2  3961.6   254.5  3971.6   254.1 4011.23  250.43  4011.6   250.4
  4031.6     250  4201.6   248.1  4231.6   248.3  4380.8   246.7 4711.29  241.75
  4711.4  241.75 4711.51  241.75  4712.1  241.74  4720.3  241.62  4780.5   241.1
  4838.1  240.69  4859.8  240.56  4918.6   240.2  4980.1  239.13  4984.2  237.53
  4985.2  237.22  4996.8  235.15  4996.9  235.13  5002.9   235.1  5004.3  235.05
  5010.6  235.12  5014.8  237.22  5015.9  238.61  5019.5  240.16  5054.1  241.61
  5139.5  243.84  5139.6  243.84  5200.4  245.91  5262.4  246.64  5262.5  246.64
  5265.2  246.61 5279.89  246.42    5280  246.42 5280.11  246.42  5297.6   246.2
  5387.6   247.4  5417.6     247  5437.6   247.7  5457.6   247.5  5467.6   246.9
  5577.6   247.4  5607.5   248.3  5607.6   248.3  5747.6   247.7  5777.6     248
  5927.6   247.8  5947.6   247.9  5967.6   247.2  6047.6   248.1  6232.5  248.37
  6457.6   248.7  6667.6   249.3  6787.2   249.1
BR U #Mann= 5
  3471.6     .99  3643.5    .055  4980.1     .08  5019.5    .055  6232.5     .06
BR U Banks=4980.1,5019.5
BR D #Sta/Elev= 63
  3471.6   256.4  3643.5  255.05  3841.6   253.5  3911.6   252.3  3931.6   252.6
  3951.6   254.2  3961.6   254.5  3971.6   254.1 4011.23  250.43  4011.6   250.4
  4031.6     250  4201.6   248.1  4231.6   248.3  4380.8   246.7 4711.29  241.75
  4711.4  241.75 4711.51  241.75  4712.1  241.74  4720.3  241.62  4780.5   241.1
  4838.1  240.69  4859.8  240.56  4918.6   240.2  4980.1  239.13  4984.2  237.53
  4985.2  237.22  4996.8  235.15  4996.9  235.13  5002.9   235.1  5004.3  235.05
  5010.6  235.12  5014.8  237.22  5015.9  238.61  5019.5  240.16  5054.1  241.61
  5139.5  243.84  5139.6  243.84  5200.4  245.91  5262.4  246.64  5262.5  246.64
  5265.2  246.61 5279.89  246.42    5280  246.42 5280.11  246.42  5297.6   246.2
  5387.6   247.4  5417.6     247  5437.6   247.7  5457.6   247.5  5467.6   246.9
  5577.6   247.4  5607.5   248.3  5607.6   248.3  5747.6   247.7  5777.6     248
  5927.6   247.8  5947.6   247.9  5967.6   247.2  6047.6   248.1  6232.5  248.37
  6457.6   248.7  6667.6   249.3  6787.2   249.1
BR D #Mann= 5
  3471.6     .99  3643.5    .055  4980.1     .08  5019.5    .055  6232.5     .06
BR D Banks=4980.1,5019.5
BC Design=,, 0 ,, 0 ,,,,,,
BC HTab HWMax=256.48

Type RM Length L Ch R = 1 ,8428.9  ,23.9,20,24.1
BEGIN DESCRIPTION:
K166-01-00-S11_UPRR-XS2
END DESCRIPTION:
XS GIS Cut Line= 4
      2943571.85     13943616.81      2942699.57     13943872.85
      2941808.42     13944088.32      2940377.43     13944502.22
#Sta/Elev= 30
  3471.6  255.86  3643.5  254.51  3911.6  251.76  3931.6  252.06  3961.6  253.96
  4011.6  249.86  4031.6  249.46  4380.8  246.16  4720.3  241.08  4980.1  238.59
  4985.2  236.68  4996.9  234.59  5004.3  234.51  5010.6  234.58  5014.8  236.68
  5015.9  238.07  5019.5  239.62  5200.4  245.37  5262.4   246.1  5297.6  245.66
  5417.6  246.46  5437.6  247.16  5467.6  246.36  5577.6  246.86  5607.5  247.76
  5947.6  247.36  5967.6  246.66  6047.6  247.56  6232.5  247.83  6787.2  248.56
#Mann= 5 ,-1 , 0
  3471.6     .99       0  3643.5    .055       0  4980.1     .08       0
  5019.5    .055       0  6232.5     .06       0
#XS Ineff= 2 , 0
       0 4982.41   241.2 5017.49       0   241.2
Permanent Ineff=
       F       F
Bank Sta=4980.1,5019.5
XS Rating Curve= 0
Exp/Cntr=.5,.3

Type RM Length L Ch R = 1 ,8408.9  ,75.7,64,57.3
BEGIN DESCRIPTION:
K166-01-00-S10_OLDWASHINGTONRD-XS3
END DESCRIPTION:
XS GIS Cut Line= 4
      2943388.76     13943662.01      2942351.26     13943934.69
      2941322.79     13944174.16      2940602.31     13943826.94
#Sta/Elev= 30
  3664.3  254.81  3764.3   253.9  3784.3  252.93  3814.3  253.44  3844.3  252.13
  3874.3  252.75  3904.3  251.34  3934.3  253.02  4024.3  250.01  4244.4  248.67
  4747.1  242.27  4754.4  241.14  4865.6  240.46  4979.9  241.11  4990.4  233.24
  5009.1   234.6  5015.8  237.64  5020.1  240.85  5294.9  242.89  5297.1  246.17
  5327.1  246.57  5357.1  245.67  5843.1  245.37  5873.1  244.07  5993.1  245.87
    6073  244.57    6173  245.19    6353  248.98    6423  249.57  6592.8  253.92
#Mann= 3 ,-1 , 0
  3664.3    .055       0  4979.9     .08       0  5020.1    .055       0
#XS Ineff= 2 , 0
       0  4980.2     242 5018.99       0     242
Permanent Ineff=
       F       F
Bank Sta=4979.9,5020.1
XS Rating Curve= 0
Exp/Cntr=.5,.3

Type RM Length L Ch R = 2 ,8376.9  ,,,
BEGIN DESCRIPTION:
OLD WASHINGTON RD
Structure ID: K166-01-00-S10; Pipeline crossing directly in front of culvert VRR
Increased the roughness value on the downstream interior cross section channel from 0.08 to 0.085 to account for the pipeline crossing the culvert. - JJA 3/16/03
END DESCRIPTION:
Bridge Culvert--1,0,-1,-1, 0
Deck Dist Width WeirC Skew NumUp NumDn MinLoCord MaxHiCord MaxSubmerge Is_Ogee
10,52,2.6,0, 50, 50, , , .95, 0, ,,,
  4244.4  4614.4  4665.5  4694.4  4714.4  4737.1  4742.6  4747.1  4753.7  4754.4
  4808.1  4811.8  4865.6  4866.4  4926.4  4930.5 4936.39  4936.5 4936.61  4979.9
  4984.2  4990.4  4995.1  5003.8  5009.1  5015.8  5020.1 5056.09  5056.2 5056.31
  5058.4  5116.7  5127.5  5189.4  5190.5  5246.7  5294.9  5297.1  5301.5  5327.1
  5357.1  5572.6    5793  5793.1  5823.1  5843.1  5873.1  5913.1  5943.1  5993.1
   248.1   243.2   242.7  242.41  242.12  241.94   241.9  241.97  242.08  242.09
  242.17  242.19  242.47  242.47  242.55  242.56  242.58  243.68  243.68  243.77
  243.78   243.8  243.81  243.83  243.84  243.85  243.86  243.94  243.94  242.84
  242.84  242.88  242.88   242.9   242.9  242.99  243.26  245.61  245.67  246.01
  245.11  244.91  244.71   244.7   244.4   244.8   243.5   244.7   244.6   245.3
   248.1   243.2  242.69   242.4   241.8   241.7   241.7   241.7  240.58  240.57
  240.19  240.16  239.89  239.89  240.19  240.21  240.25  240.25  240.25  240.54
  237.03  232.67  233.07  234.19  234.03  237.07  240.28  240.81  240.81  240.81
  240.84  240.84  240.84  241.21  241.22  241.81  242.32   245.6  245.66     246
   245.1   244.9   244.7   244.7   244.4   244.8   243.5   244.7   244.6   245.3
  4244.4  4614.4  4665.5  4694.4  4714.4  4737.1  4742.6  4747.1  4753.7  4754.4
  4808.1  4811.8  4865.6  4866.4  4926.4  4930.5 4936.39  4936.5 4936.61  4979.9
  4984.2  4990.4  4995.1  5003.8  5009.1  5015.8  5020.1 5056.09  5056.2 5056.31
  5058.4  5116.7  5127.5  5189.4  5190.5  5246.7  5294.9  5297.1  5301.5  5327.1
  5357.1  5572.6    5793  5793.1  5823.1  5843.1  5873.1  5913.1  5943.1  5993.1
   248.1   243.2   242.7  242.41  242.12  241.94   241.9  241.97  242.08  242.09
  242.17  242.19  242.47  242.47  242.55  242.56  242.58  243.68  243.68  243.77
  243.78   243.8  243.81  243.83  243.84  243.85  243.86  243.94  243.94  242.84
  242.84  242.88  242.88   242.9   242.9  242.99  243.26  245.61  245.67  246.01
  245.11  244.91  244.71   244.7   244.4   244.8   243.5   244.7   244.6   245.3
   248.1   243.2  242.69   242.4   241.8   241.7   241.7   241.7  240.58  240.57
  240.19  240.16  239.89  239.89  240.19  240.21  240.25  240.25  240.25  240.54
  237.03  232.67  233.07  234.19  234.03  237.07  240.28  240.81  240.81  240.81
  240.84  240.84  240.84  241.21  241.22  241.81  242.32   245.6  245.66     246
   245.1   244.9   244.7   244.7   244.4   244.8   243.5   244.7   244.6   245.3
BR Coef= 1 , 0 , 0 ,1.25, 0 ,,,.8,0,2,0,
WSPro=,,,, 1 ,,,, 0 ,,,, 0 ,,,,-1 ,-1 ,-1 , 0 , 0 , 0 , 0 , 0
Culvert=2,8,8,52,.013,.7,1,8,3,232.48,4994.2,232.41,4994.2,Culvert #1  , 0 ,10
Culvert Bottom n=.013
Culvert=2,8,8,52,.013,.7,1,8,3,232.42,5005,232.46,5005,Culvert #2  , 0 ,10
Culvert Bottom n=.013
BR U #Sta/Elev= 50
  4244.4   248.1  4614.4   243.2  4665.5  242.69  4694.4   242.4  4714.4   241.8
  4737.1   241.7  4742.6   241.7  4747.1   241.7  4753.7  240.58  4754.4  240.57
  4808.1  240.19  4811.8  240.16  4865.6  239.89  4866.4  239.89  4926.4  240.19
  4930.5  240.21 4936.39  240.25  4936.5  240.25 4936.61  240.25  4979.9  240.54
  4984.2  237.03  4990.4  232.67  4995.1  233.07  5003.8  234.19  5009.1  234.03
  5015.8  237.07  5020.1  240.28 5056.09  240.81  5056.2  240.81 5056.31  240.81
  5058.4  240.84  5116.7  240.84  5127.5  240.84  5189.4  241.21  5190.5  241.22
  5246.7  241.81  5294.9  242.32  5297.1   245.6  5301.5  245.66  5327.1     246
  5357.1   245.1  5572.6   244.9    5793   244.7  5793.1   244.7  5823.1   244.4
  5843.1   244.8  5873.1   243.5  5913.1   244.7  5943.1   244.6  5993.1   245.3
BR U #Mann= 3
  4244.4    .055  4979.9     .08  5020.1    .055
BR U Banks=4979.9,5020.1
BR D #Sta/Elev= 50
  4244.4   248.1  4614.4   243.2  4665.5  242.69  4694.4   242.4  4714.4   241.8
  4737.1   241.7  4742.6   241.7  4747.1   241.7  4753.7  240.58  4754.4  240.57
  4808.1  240.19  4811.8  240.16  4865.6  239.89  4866.4  239.89  4926.4  240.19
  4930.5  240.21 4936.39  240.25  4936.5  240.25 4936.61  240.25  4979.9  240.54
  4984.2  237.03  4990.4  232.67  4995.1  233.07  5003.8  234.19  5009.1  234.03
  5015.8  237.07  5020.1  240.28 5056.09  240.81  5056.2  240.81 5056.31  240.81
  5058.4  240.84  5116.7  240.84  5127.5  240.84  5189.4  241.21  5190.5  241.22
  5246.7  241.81  5294.9  242.32  5297.1   245.6  5301.5  245.66  5327.1     246
  5357.1   245.1  5572.6   244.9    5793   244.7  5793.1   244.7  5823.1   244.4
  5843.1   244.8  5873.1   243.5  5913.1   244.7  5943.1   244.6  5993.1   245.3
BR D #Mann= 3
  4244.4    .055  4979.9     .08  5020.1    .055
BR D Banks=4979.9,5020.1
BC Design=,, 0 ,, 0 ,,,,,,
BC HTab HWMax=254.81

Type RM Length L Ch R = 1 ,8344.9  ,218.8,217.3,122
BEGIN DESCRIPTION:
K166-01-00-S10_OLDWASHINGTONRD-XS2
END DESCRIPTION:
XS GIS Cut Line= 4
      2943381.38     13943604.93      2942343.94      13943877.6
      2941317.26     13944116.65      2940598.36     13943770.19
#Sta/Elev= 30
  3664.3  254.81  3764.3   253.9  3784.3  252.93  3814.3  253.44  3844.3  252.13
  3874.3  252.75  3904.3  251.34  3934.3  253.02  4024.3  250.01  4244.4  248.67
  4747.1  242.27  4754.4  241.14  4865.6  240.46  4979.9  241.11  4990.4  233.24
  5009.1   234.6  5015.8  237.64  5020.1  240.85  5294.9  242.89  5297.1  246.17
  5327.1  246.57  5357.1  245.67  5843.1  245.37  5873.1  244.07  5993.1  245.87
    6073  244.57    6173  245.19    6353  248.98    6423  249.57  6592.8  253.92
#Mann= 3 ,-1 , 0
  3664.3    .055       0  4979.9     .08       0  5020.1    .055       0
#XS Ineff= 2 , 0
       0  4980.2   239.2 5018.99       0   239.2
Permanent Ineff=
       F       F
Bank Sta=4979.9,5020.1
XS Rating Curve= 0
Exp/Cntr=.5,.3

Type RM Length L Ch R = 1 ,8127.6  ,572.2,559.1,530.4
BEGIN DESCRIPTION:
K166-01-00-S10_OLDWASHINGTONRD-XS1
LIDAR overbanks, interpolated channel
END DESCRIPTION:
XS GIS Cut Line= 4
      2942890.16     13943612.89      2942279.65     13943773.34
      2941252.97      13944012.4       2940657.3     13943725.58
#Sta/Elev= 30
  4298.4   251.4  4318.4  250.36  4498.4  249.56  4578.4  248.24  4678.4  246.46
  4818.4  242.73  4858.4   242.3  4888.4   240.5  4918.4  240.69  4968.4  239.62
 4974.66  237.49 4993.03  232.89 5007.94  234.58 5013.28  236.93 5016.71  239.34
  5119.6   239.4  5249.6  241.23  5339.6  240.86  5399.6  241.77  5429.6  241.13
  5609.6  243.32  5709.6  242.14  5939.6  242.64  5949.6   242.2  5993.8  243.74
  6023.8  243.14  6073.8  243.74  6143.8  243.13  6363.8  246.93  6644.9  255.19
#Mann= 5 ,-1 , 0
  4298.4     .06       0  4818.4     .08       0  4918.4    .055       0
  4968.4    .055       0 5016.71     .06       0
Bank Sta=4968.4,5016.71
XS Rating Curve= 0
Exp/Cntr=.3,.1

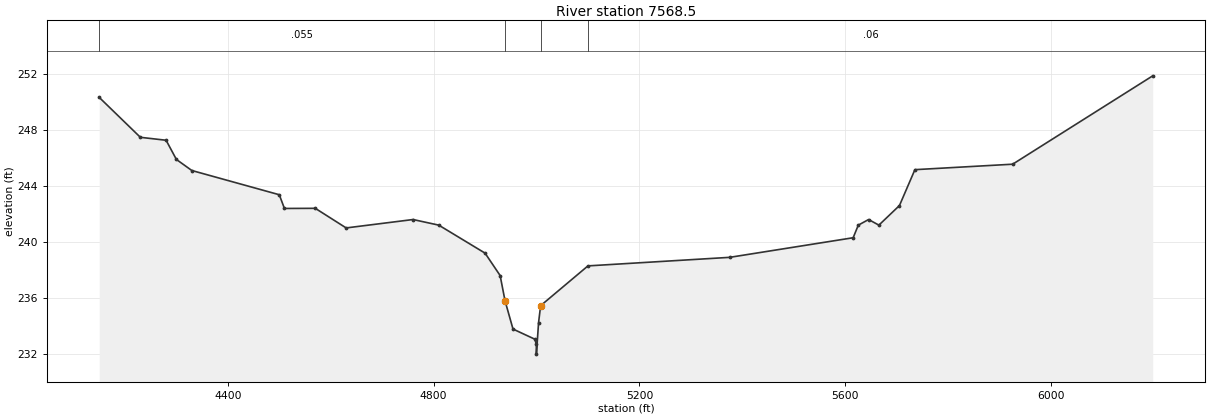
Type RM Length L Ch R = 1 ,7568.5  ,898.6,1012.6,989.1
BEGIN DESCRIPTION:
Cross Section K166-01-00-X43
END DESCRIPTION:
XS GIS Cut Line= 4
      2942690.45     13942950.57      2941994.22     13943277.75
      2941831.06     13943386.76      2940772.05     13943610.29
#Sta/Elev= 30
    4150  250.32    4230  247.47    4280  247.26    4300  245.89    4330   245.1
    4500  243.37    4510  242.39    4570   242.4    4630     241    4760   241.6
    4810   241.2    4900   239.2  4929.3   237.6  4938.8   235.8  4954.3  233.78
  4996.5  233.06  4999.6  232.72  4999.8  231.99    5004  234.24    5008  235.45
    5100  238.29  5375.5   238.9  5615.5   240.3  5625.5   241.2  5645.5   241.6
  5665.5   241.2  5705.5   242.6  5735.5  245.16  5925.5  245.55  6197.8  251.86
#Mann= 4 ,-1 , 0
    4150    .055       0  4938.8     .08       0    5008    .055       0
    5100     .06       0
Bank Sta=4938.8,5008
XS Rating Curve= 0
Exp/Cntr=.3,.1