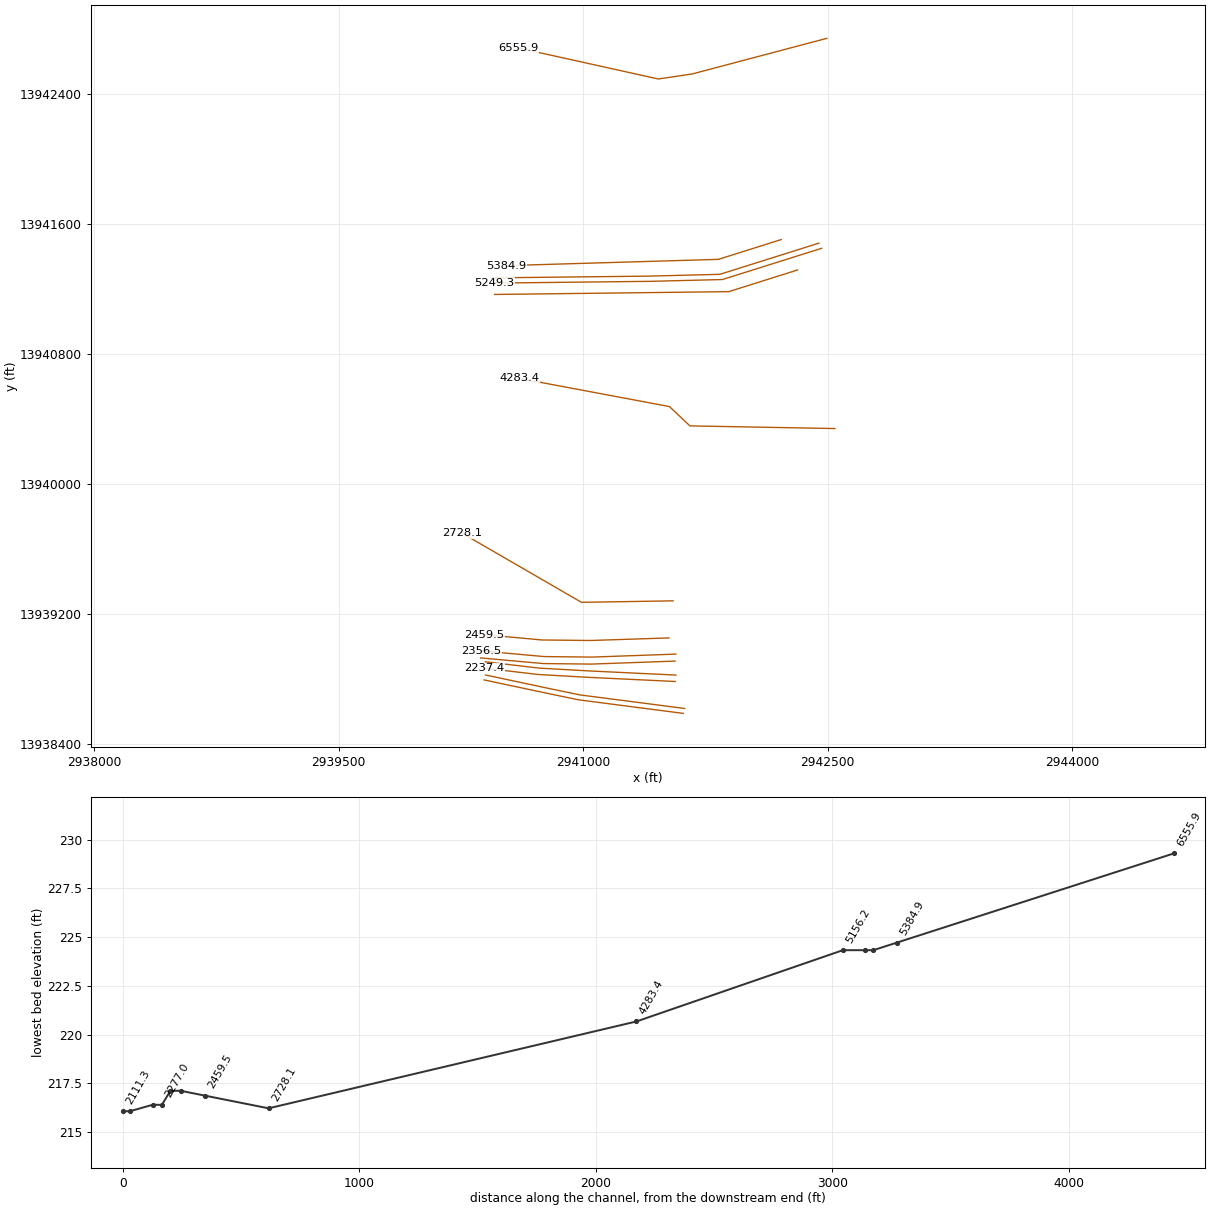
HEC-RAS study K166-01-00.prj: K166-01-00

--- K166-01-00.g01 (geometry) --- (continued)

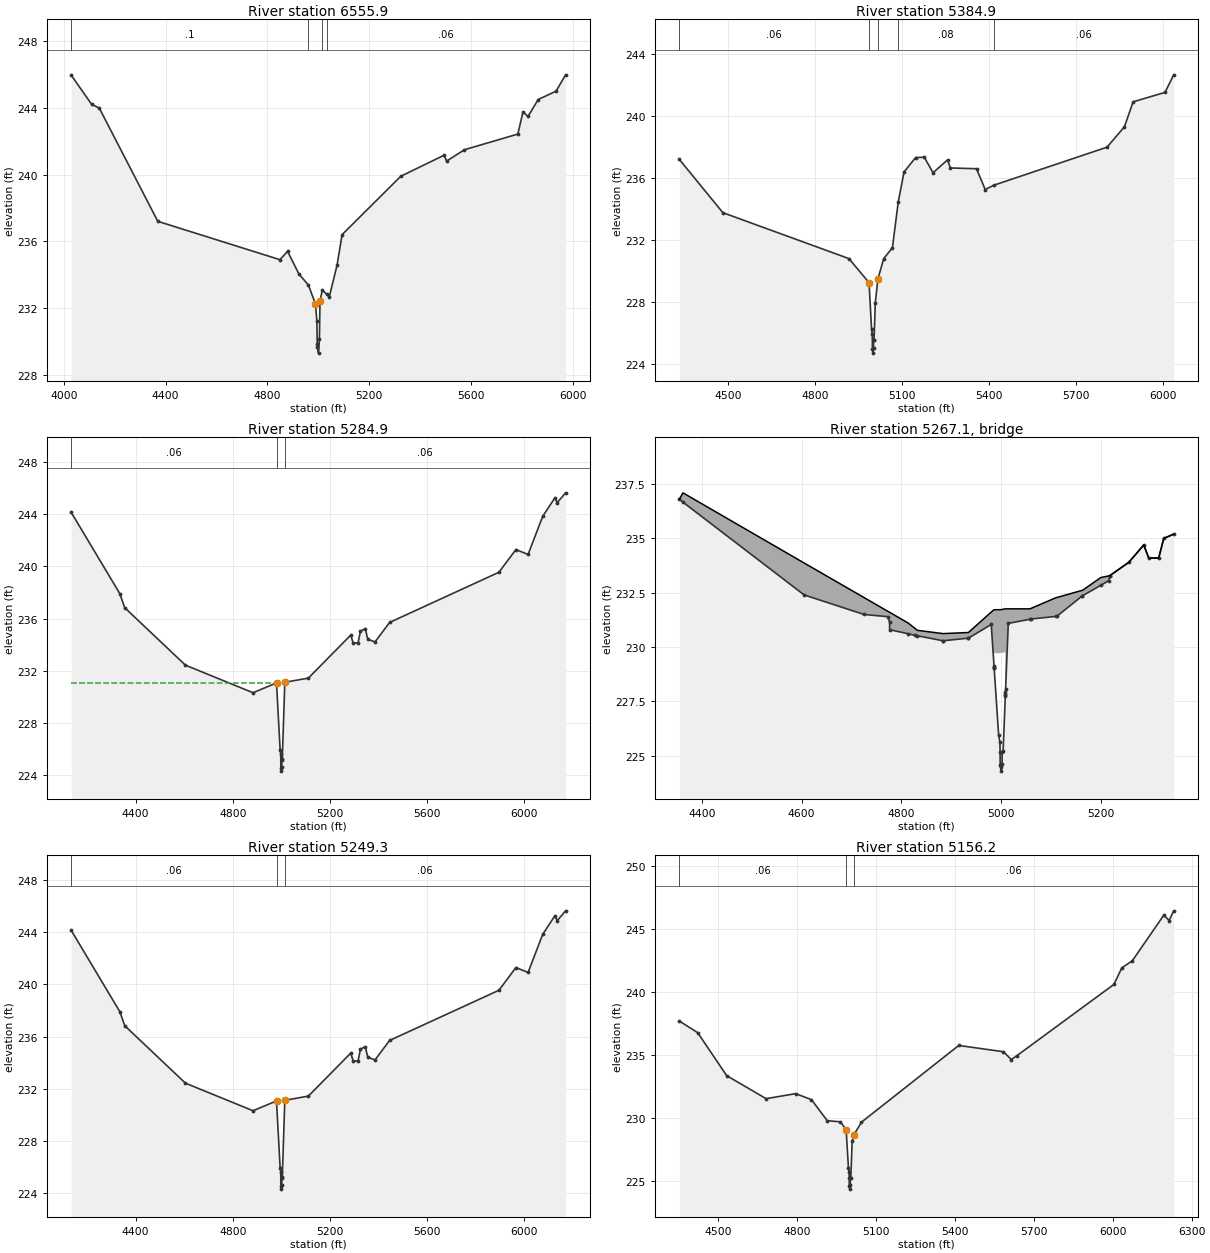
Type RM Length L Ch R = 1 ,6555.9  ,1184.4,1171,1127.9
BEGIN DESCRIPTION:
Cross Section K166-01-00-X42
Moved bank stations from 4961.7 to 4988.9 and from 5016.1 to 5006.9. - JJA 3/16/03
END DESCRIPTION:
XS GIS Cut Line= 4
      2942495.14     13942741.37      2941669.62     13942522.62
      2941461.28     13942491.37      2940604.51     13942681.47
#Sta/Elev= 30
  4029.6  245.96  4109.6  244.21  4139.6  243.99  4369.6   237.2  4849.6   234.9
  4879.6   235.4  4923.8  234.05  4961.7  233.37  4988.9  232.25  4994.6  231.22
    4996  229.87  4996.7  229.64  5001.1   229.3  5004.6  230.12  5006.9  232.43
  5016.1  233.08  5033.6  232.82  5043.4  232.67  5074.1  234.58  5093.6   236.4
  5324.3   239.9  5494.3  241.16  5504.3  240.81  5574.3  241.49  5784.3  242.43
  5804.3  243.75  5824.3  243.49  5864.3   244.5  5934.3     245  5971.9  245.98
#Mann= 4 ,-1 , 0
  4029.6      .1       0  4961.7     .08       0  5016.1     .08       0
  5033.6     .06       0
Bank Sta=4988.9,5006.9
XS Rating Curve= 0
Exp/Cntr=.3,.1

Type RM Length L Ch R = 1 ,5384.9  ,104.1,100,100.8
BEGIN DESCRIPTION:
K166-01-00-S9_ROSSRD-XS4
LIDAR overbanks, interpolated channel
END DESCRIPTION:
XS GIS Cut Line= 3
      2942215.17     13941503.93      2941829.25     13941382.15
       2940529.9     13941343.69
#Sta/Elev= 30
  4332.4   237.2  4482.4  233.77  4917.1  230.81 4986.51  229.26 4995.23  226.25
 4997.65  225.95 4998.14  224.97 5000.36  224.72 5001.89  225.05 5001.98  225.54
  5003.8  225.57 5007.99  227.95  5017.1   229.5  5037.1  230.81  5067.1  231.51
  5087.1  234.44  5107.1  236.39  5147.1  237.32  5177.1  237.34  5207.1  236.34
  5257.1  237.17  5267.1  236.65  5357.1   236.6  5387.1  235.26  5417.1  235.54
  5807.1  237.99  5867.1   239.3  5897.1  240.91  6007.1  241.52    6037  242.65
#Mann= 5 ,-1 , 0
  4332.4     .06       0 4986.51     .07       0  5017.1     .06       0
  5087.1     .08       0  5417.1     .06       0
Bank Sta=4986.51,5017.1
XS Rating Curve= 0
Exp/Cntr=.5,.3

Type RM Length L Ch R = 1 ,5284.9  ,36.7,35.6,35.9
BEGIN DESCRIPTION:
K166-01-00-S9_ROSSRD-XS3
END DESCRIPTION:
XS GIS Cut Line= 4
      2942446.33     13941481.88      2941838.46     13941290.06
      2941395.55     13941278.96      2940441.13     13941268.34
#Sta/Elev= 30
  4135.2  244.13  4335.2  237.91  4355.2  236.84  4605.2  232.44  4883.5  230.33
  4980.1  231.08    4995  225.98  4997.5  225.66 4998.01   224.6  5000.3  224.33
  5001.9  224.68    5002  225.21  5003.9  225.24  5014.3  231.13  5111.3  231.45
  5285.7  234.74  5295.7  234.14  5315.7  234.14  5325.7  235.04  5345.7  235.24
  5355.7  234.42  5385.7  234.22  5445.7  235.71  5895.7  239.55  5965.7  241.29
  6015.7  240.91  6075.7  243.82  6125.7  245.24  6135.7  244.88  6170.2  245.63
#Mann= 3 ,-1 , 0
  4135.2     .06       0  4980.1     .07       0  5014.3     .06       0
#XS Ineff= 2 , 0
       0  4970.1   231.1  5024.3       0   231.1
Permanent Ineff=
       F       F
Bank Sta=4980.1,5014.3
XS Rating Curve= 0
Exp/Cntr=.5,.3

Type RM Length L Ch R = 3 ,5267.1  ,,,
BEGIN DESCRIPTION:
ROSS ROAD
Structure ID: K166-01-00-S9
END DESCRIPTION:
Bridge Culvert--1,0,-1,-1, 0
Deck Dist Width WeirC Skew NumUp NumDn MinLoCord MaxHiCord MaxSubmerge Is_Ogee
10,18,2.6,0, 50, 50, , , .95, 0, ,,,
  4355.2  4362.4  4605.2  4725.2  4772.6  4776.4  4776.6  4814.1  4826.7  4832.2
  4883.5  4883.6  4934.3  4934.4  4980.1  4985.7 4985.81  4985.9    4986    4995
  4997.5  4997.9 4998.01  4998.8  5000.3  5001.9    5002  5003.9  5008.3 5008.39
  5008.5  5008.6  5008.9  5014.3  5057.4  5058.8  5109.5  5111.3  5162.2  5162.9
  5199.5  5216.1 5217.11  5217.2  5255.7  5285.7  5295.7  5315.7  5325.7  5345.7
   236.8   237.1  233.87  232.28  231.65   231.6   231.6   231.1  230.87  230.77
  230.62  230.62  230.67  230.67  231.61  231.72  231.72  231.72  231.72  231.72
  231.72  231.72  231.72  231.72  231.73  231.73  231.73  231.74  231.76  231.76
  231.76  231.76  231.76  231.76  231.76  231.77  232.27  232.28  232.61  232.61
   233.2  233.28  233.28  233.28   233.9   234.7   234.1   234.1     235   235.2
   236.8  236.67   232.4   231.5   231.4  231.16   230.8  230.61  230.54  230.52
  230.29  230.29  230.41  230.41  231.04  229.12  229.09  229.72  229.72  229.72
  229.72  229.72  229.72  229.72  229.73  229.73  229.73  229.74  229.76  229.76
  227.85  227.91  228.08  231.09  231.28  231.29  231.41  231.41  232.35  232.36
  232.84  233.06  233.26  233.28   233.9   234.7   234.1   234.1     235   235.2
  4355.2  4362.4  4605.2  4725.2  4772.6  4776.4  4776.6  4814.1  4826.7  4832.2
  4883.5  4883.6  4934.3  4934.4  4980.1  4985.7 4985.81  4985.9    4986    4995
  4997.5  4997.9 4998.01  4998.8  5000.3  5001.9    5002  5003.9  5008.3 5008.39
  5008.5  5008.6  5008.9  5014.3  5057.4  5058.8  5109.5  5111.3  5162.2  5162.9
  5199.5  5216.1 5217.11  5217.2  5255.7  5285.7  5295.7  5315.7  5325.7  5345.7
   236.8   237.1  233.87  232.28  231.65   231.6   231.6   231.1  230.87  230.77
  230.62  230.62  230.67  230.67  231.61  231.72  231.72  231.72  231.72  231.72
  231.72  231.72  231.72  231.72  231.73  231.73  231.73  231.74  231.76  231.76
  231.76  231.76  231.76  231.76  231.76  231.77  232.27  232.28  232.61  232.61
   233.2  233.28  233.28  233.28   233.9   234.7   234.1   234.1     235   235.2
  236.71  236.58  232.31  231.41  231.31  231.07  230.71  230.52  230.45  230.43
   230.2   230.2  230.32  230.32  230.95  229.03     229  229.63  229.63  229.63
  229.63  229.63  229.63  229.63  229.64  229.64  229.64  229.65  229.67  229.67
  227.76  227.82  227.99     231  231.19   231.2  231.32  231.32  232.26  232.27
  232.75  232.97  233.17  233.19  233.81  234.61  234.01  234.01  234.91  235.11
BR Coef= 1 , 1 , 0 ,1.25, 0 ,,,.8,0,2,0,
WSPro=,,,, 1 ,,,, 0 ,,,, 0 ,,,,-1 ,-1 ,-1 , 0 , 0 , 0 , 0 , 0
BR U #Sta/Elev= 50
  4355.2   236.8  4362.4  236.67  4605.2   232.4  4725.2   231.5  4772.6   231.4
  4776.4  231.16  4776.6   230.8  4814.1  230.61  4826.7  230.54  4832.2  230.52
  4883.5  230.29  4883.6  230.29  4934.3  230.41  4934.4  230.41  4980.1  231.04
  4985.7  229.12 4985.81  229.09  4985.9  229.05    4986  229.02    4995  225.94
  4997.5  225.62  4997.9  225.18 4998.01  224.56  4998.8  224.47  5000.3  224.29
  5001.9  224.64    5002  225.17  5003.9   225.2  5008.3  227.73 5008.39  227.79
  5008.5  227.85  5008.6  227.91  5008.9  228.08  5014.3  231.09  5057.4  231.28
  5058.8  231.29  5109.5  231.41  5111.3  231.41  5162.2  232.35  5162.9  232.36
  5199.5  232.84  5216.1  233.06 5217.11  233.26  5217.2  233.28  5255.7   233.9
  5285.7   234.7  5295.7   234.1  5315.7   234.1  5325.7     235  5345.7   235.2
BR U #Mann= 3
  4355.2     .06  4980.1     .07  5014.3     .06
BR U Banks=4980.1,5014.3
BR D #Sta/Elev= 50
  4355.2   236.8  4362.4  236.67  4605.2   232.4  4725.2   231.5  4772.6   231.4
  4776.4  231.16  4776.6   230.8  4814.1  230.61  4826.7  230.54  4832.2  230.52
  4883.5  230.29  4883.6  230.29  4934.3  230.41  4934.4  230.41  4980.1  231.04
  4985.7  229.12 4985.81  229.09  4985.9  229.05    4986  229.02    4995  225.94
  4997.5  225.62  4997.9  225.18 4998.01  224.56  4998.8  224.47  5000.3  224.29
  5001.9  224.64    5002  225.17  5003.9   225.2  5008.3  227.73 5008.39  227.79
  5008.5  227.85  5008.6  227.91  5008.9  228.08  5014.3  231.09  5057.4  231.28
  5058.8  231.29  5109.5  231.41  5111.3  231.41  5162.2  232.35  5162.9  232.36
  5199.5  232.84  5216.1  233.06 5217.11  233.26  5217.2  233.28  5255.7   233.9
  5285.7   234.7  5295.7   234.1  5315.7   234.1  5325.7     235  5345.7   235.2
BR D #Mann= 3
  4355.2     .06  4980.1     .07  5014.3     .06
BR D Banks=4980.1,5014.3
BC Design=,, 0 ,, 0 ,,,,,,
BC HTab HWMax=245.7

Type RM Length L Ch R = 1 ,5249.3  ,84.7,93.1,74.9
BEGIN DESCRIPTION:
K166-01-00-S9_ROSSRD-XS2
END DESCRIPTION:
XS GIS Cut Line= 4
      2942462.95     13941450.12       2941854.4     13941258.08
      2941410.75     13941246.97      2940456.29     13941236.34
#Sta/Elev= 30
  4135.2  244.13  4335.2  237.91  4355.2  236.84  4605.2  232.44  4883.5  230.33
  4980.1  231.08    4995  225.98  4997.5  225.66 4998.01   224.6  5000.3  224.33
  5001.9  224.68    5002  225.21  5003.9  225.24  5014.3  231.13  5111.3  231.45
  5285.7  234.74  5295.7  234.14  5315.7  234.14  5325.7  235.04  5345.7  235.24
  5355.7  234.42  5385.7  234.22  5445.7  235.71  5895.7  239.55  5965.7  241.29
  6015.7  240.91  6075.7  243.82  6125.7  245.24  6135.7  244.88  6170.2  245.63
#Mann= 3 ,-1 , 0
  4135.2     .06       0  4980.1     .07       0  5014.3     .06       0
#XS Ineff= 2 , 0
       0 4973.43   229.6 5020.97       0   229.6
Permanent Ineff=
       F       F
Bank Sta=4980.1,5014.3
XS Rating Curve= 0
Exp/Cntr=.5,.3

Type RM Length L Ch R = 1 ,5156.2  ,889.3,872.8,772.4
BEGIN DESCRIPTION:
K166-01-00-S9_ROSSRD-XS1
LIDAR overbanks, interpolated channel
END DESCRIPTION:
XS GIS Cut Line= 3
        2942315.     13941316.78      2941893.01     13941183.61
      2940455.73     13941166.33
#Sta/Elev= 30
  4351.8  237.69  4421.8  236.76  4531.8  233.35  4681.8  231.52  4794.3  231.92
  4854.3  231.44  4914.3  229.77  4964.3  229.68    4986  229.06    4995  225.98
  4997.5  225.66  4997.9  225.22 4998.01   224.6  5000.3  224.33  5001.9  224.68
    5002  225.21  5003.9  225.24  5008.9  228.12  5014.3  228.61  5044.3  229.65
  5414.3  235.75  5584.3  235.25  5614.3  234.63  5634.3  234.92  6004.3   240.6
  6034.3  241.91  6074.3  242.48  6194.3  246.11  6214.3  245.68  6231.7  246.45
#Mann= 3 ,-1 , 0
  4351.8     .06       0    4986     .07       0  5014.3     .06       0
Bank Sta=4986,5014.3
XS Rating Curve= 0
Exp/Cntr=.3,.1

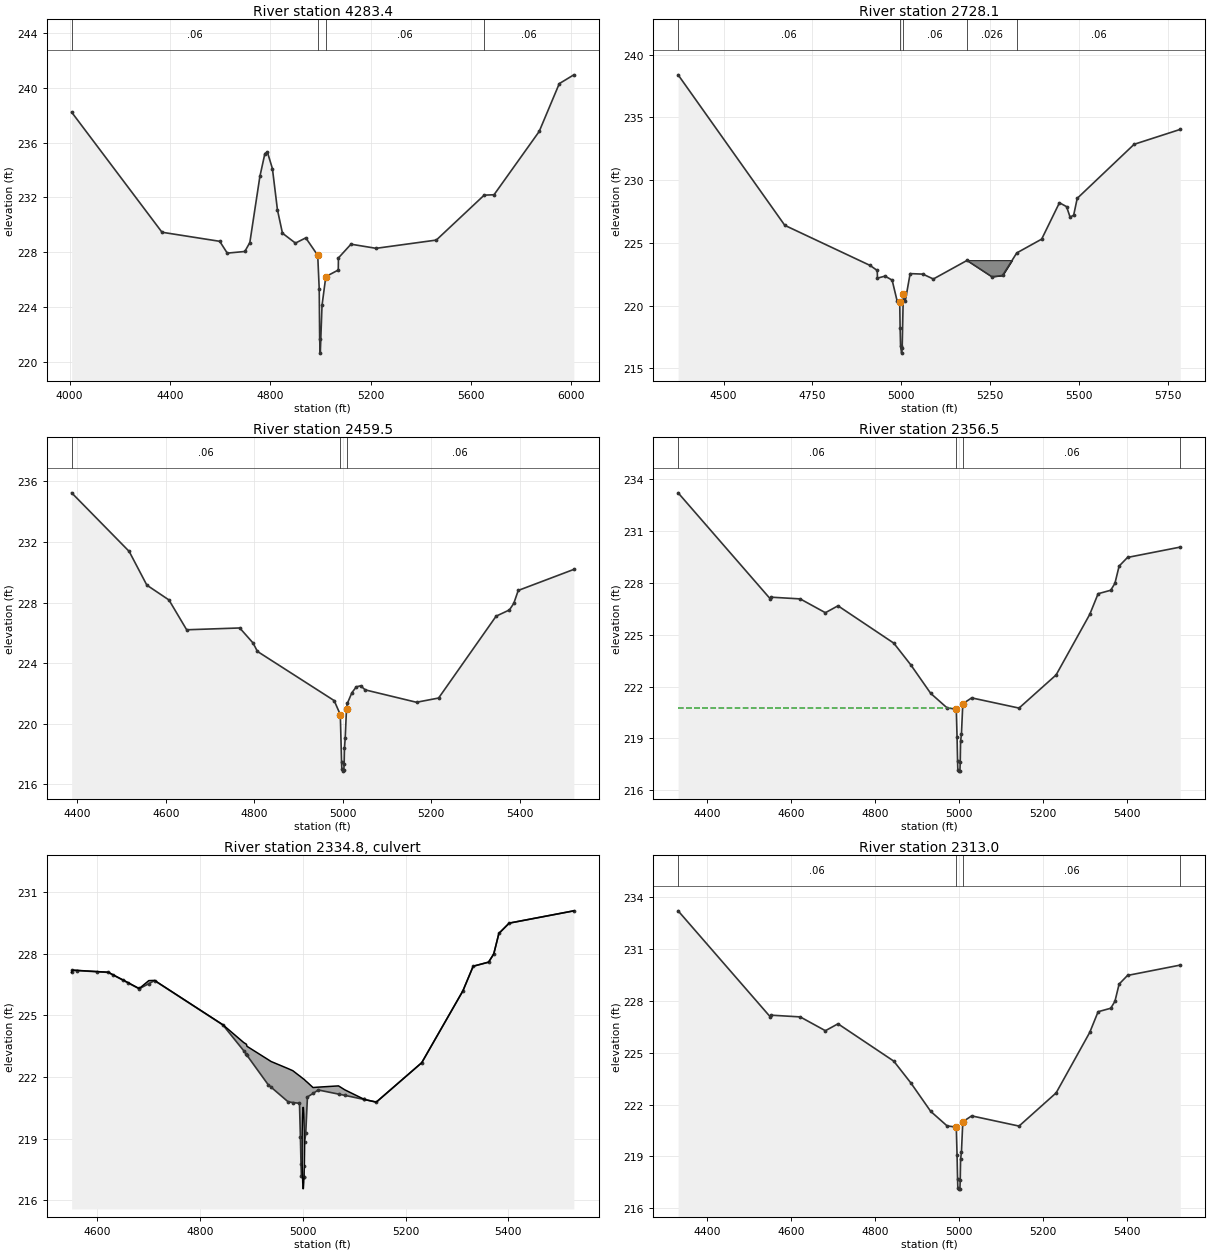
Type RM Length L Ch R = 1 ,4283.4  ,1411.4,1555.3,1404.2
BEGIN DESCRIPTION:
Cross Section K166-01-00-X41
END DESCRIPTION:
XS GIS Cut Line= 4
      2942544.49     13940341.66      2941654.74     13940358.07
      2941528.99     13940476.98      2940607.12     13940650.22
#Sta/Elev= 30
  4008.5  238.21  4368.5  229.47  4598.5  228.81  4628.5  227.95  4698.5  228.07
  4718.5  228.72  4758.5  233.53  4778.5   235.2  4788.5   235.3  4808.5   234.1
  4828.5   231.1  4848.5   229.4  4900.2  228.68  4941.4  229.06    4989  227.79
    4995  225.31  4996.7  221.69  4999.2  220.67  5006.1  224.14  5021.2  226.24
  5070.9  226.72  5071.5   227.6  5121.5   228.6  5221.5   228.3  5461.5   228.9
  5652.2  232.17  5691.5   232.2  5871.5  236.81  5951.5  240.29  6009.5  240.93
#Mann= 4 ,-1 , 0
  4008.5     .06       0    4989     .07       0  5021.2     .06       0
  5652.2     .06       0
Bank Sta=4989,5021.2
XS Rating Curve= 0
Exp/Cntr=.3,.1

Type RM Length L Ch R = 1 ,2728.1  ,242.3,268.6,328.7
BEGIN DESCRIPTION:
Cross Section K166-01-00-X40
Added blocked obstruction for pond area on right overbank shown on new sid image and 0.026 for manning n - JJA 3/16/03
END DESCRIPTION:
XS GIS Cut Line= 3
      2941551.48     13939282.12       2940989.1     13939272.99
      2940254.04      13939699.5
#Sta/Elev= 30
  4372.3   238.4  4672.3   226.4  4912.3   223.2  4932.3   222.8  4932.9  222.19
  4954.3  222.35  4974.2  222.03  4988.3  220.36  4995.5  220.29  4996.6  218.25
  4997.9  216.76  5000.8  216.21  5002.4  216.58  5005.6  220.92  5011.2  220.37
  5024.8  222.55  5060.5  222.51  5090.1  222.12  5184.7   223.6  5254.7   222.3
  5284.7   222.4  5324.7   224.2  5394.7   225.3  5444.7   228.2  5464.7  227.89
  5474.7  227.05  5484.7  227.21  5494.7  228.55  5654.7  232.86  5784.6  234.05
#Mann= 5 ,-1 , 0
  4372.3     .06       0  4995.5     .07       0  5005.6     .06       0
  5184.7    .026       0  5324.7     .06       0
#Block Obstruct= 2 ,-1
 5185.02  5316.3  223.62 5315.42  5444.7  223.76
Bank Sta=4995.5,5005.6
XS Rating Curve= 0
Exp/Cntr=.3,.1

Type RM Length L Ch R = 1 ,2459.5  ,103.1,103,101.9
BEGIN DESCRIPTION:
K166-01-00-S8_PRIVATEACCESS-XS4
LIDAR overbanks, interpolated channel
END DESCRIPTION:
XS GIS Cut Line= 4
      2941526.36     13939054.09      2941043.14     13939038.27
      2940747.06     13939041.48      2940392.79     13939073.85
#Sta/Elev= 30
  4386.9  235.25  4516.9  231.38  4556.9  229.15  4606.9  228.17  4646.9   226.2
  4766.9  226.32  4796.9  225.33  4806.9  224.77  4980.4  221.52 4994.27  220.59
  4997.1  217.46 4997.77  217.01 5000.51  216.86 5002.26  216.94 5002.95  217.35
 5003.65  218.36  5005.4  219.08 5008.27  220.99  5010.4  221.35  5020.4  222.04
  5030.4  222.43  5040.4   222.5  5050.4  222.23  5166.5  221.41  5216.5  221.69
  5346.5   227.1  5376.5  227.51  5386.5  227.95  5396.5   228.8  5522.2  230.19
#Mann= 3 ,-1 , 0
  4386.9     .06       0 4994.27      .1       0 5008.27     .06       0
Bank Sta=4994.27,5008.27
XS Rating Curve= 0
Exp/Cntr=.5,.3

Type RM Length L Ch R = 1 ,2356.5  ,43.6,43.5,43.1
BEGIN DESCRIPTION:
K166-01-00-S8_PRIVATEACCESS-XS3
END DESCRIPTION:
XS GIS Cut Line= 4
      2941568.52     13938954.54      2941055.55     13938936.22
      2940759.47     13938939.43      2940375.34     13938974.19
#Sta/Elev= 30
  4331.4  233.22  4550.9  227.08  4552.1  227.18  4622.1  227.08  4682.1  226.28
  4712.1  226.68  4844.9  224.52  4885.5  223.26  4932.9  221.61  4971.9  220.77
  4993.8   220.7  4995.6  219.08  4996.8  217.72  4997.5  217.15  5000.4  217.11
  5002.4  217.12  5003.2  217.65    5004  218.84    5006  219.24  5009.3  221.01
  5030.4  221.35  5143.2  220.76  5231.5  222.68  5311.5  226.18  5331.5  227.38
  5361.5  227.58  5371.5  227.98  5381.5  228.98  5401.5  229.48  5527.2  230.08
#Mann= 4 ,-1 , 0
  4331.4     .06       0  4993.8      .1       0  5009.3     .06       0
  5527.2     .99       0
#XS Ineff= 2 , 0
       0  4989.1  220.78  5013.1       0  220.78
Permanent Ineff=
       F       F
Bank Sta=4993.8,5009.3
XS Rating Curve= 0
Exp/Cntr=.5,.3

Type RM Length L Ch R = 2 ,2334.8  ,,,
BEGIN DESCRIPTION:
PRIVATE ACCESS 2000' US FROM PENICK
Structure ID: K166-01-00-S8; CMP projecting from fill VRR
END DESCRIPTION:
Bridge Culvert--1,0,-1,-1, 0
Deck Dist Width WeirC Skew NumUp NumDn MinLoCord MaxHiCord MaxSubmerge Is_Ogee
10,25,3,0, 46, 46, , , .95, 0, ,,,
  4550.9  4552.1  4560.9  4600.9  4622.1  4630.9  4650.9  4660.9  4680.9  4682.1
  4700.9  4712.1  4844.9  4885.5  4890.7  4891.7  4932.9  4938.5  4971.9  4980.9
  4993.8  4995.6  4996.8  4997.5  5000.4  5002.2  5002.4  5003.2    5004    5006
  5009.3  5020.1  5030.4  5069.7  5081.8  5119.2  5119.6  5143.2  5231.5  5311.5
  5331.5  5361.5  5371.5  5381.5  5401.5  5527.2
   227.1  227.21   227.2  227.14  227.11  226.99  226.73   226.6  226.33  226.31
   226.7  226.71  224.55  223.68   223.6   223.5  222.85  222.76  222.41  222.31
  222.06  222.03     222  221.99  221.93   221.9   221.9  221.88  221.86  221.81
  221.74  221.49  221.51  221.57  221.38  220.92  220.91  220.78   222.7   226.2
   227.4   227.6     228     229   229.5   230.1
   227.1   227.2  227.19  227.13   227.1  226.98  226.72  226.58  226.32   226.3
  226.55   226.7  224.54  223.28   223.1  223.06  221.63  221.51  220.79  220.76
  220.72   219.1  217.74  217.17  217.13  217.14  217.14  217.67  218.86  219.26
  221.03   221.2  221.37  221.17  221.11  220.91  220.91  220.78   222.7   226.2
   227.4   227.6     228     229   229.5   230.1
  4550.9  4552.1  4560.9  4600.9  4622.1  4630.9  4650.9  4660.9  4680.9  4682.1
  4700.9  4712.1  4844.9  4885.5  4890.7  4891.7  4932.9  4938.5  4971.9  4980.9
  4993.8  4995.6  4996.8  4997.5  5000.4  5002.2  5002.4  5003.2    5004    5006
  5009.3  5020.1  5030.4  5069.7  5081.8  5119.2  5119.6  5143.2  5231.5  5311.5
  5331.5  5361.5  5371.5  5381.5  5401.5  5527.2
   227.1  227.21   227.2  227.14  227.11  226.99  226.73   226.6  226.33  226.31
   226.7  226.71  224.55  223.68   223.6   223.5  222.85  222.76  222.41  222.31
  222.06  222.03     222  221.99  221.93   221.9   221.9  221.88  221.86  221.81
  221.74  221.49  221.51  221.57  221.38  220.92  220.91  220.78   222.7   226.2
   227.4   227.6     228     229   229.5   230.1
  225.96  226.06  226.05  225.99  225.96  225.84  225.58  225.44  225.18  225.16
  225.41  225.56   223.4  222.14  221.96  221.92  220.49  220.37  219.65  219.62
  219.58  217.96   216.6  216.03  215.99     216     216  216.53  217.72  218.12
  219.89  220.06  220.23  220.03  219.97  219.77  219.77  219.64  221.56  225.06
  226.26  226.46  226.86  227.86  228.36  228.96
BR Coef= 1 , 0 , 0 ,1.25, 0 ,,,.8,-1,2,0,
WSPro=,,,, 1 ,,,, 0 ,,,, 0 ,,,,-1 ,-1 ,-1 , 0 , 0 , 0 , 0 , 0
Culvert=1,4,,25,.026,.9,1,2,3,216.54,5001.1,216.14,5001.1,Culvert #1  , 0 ,10
Culvert Bottom n=.026
BR U #Sta/Elev= 46
  4550.9   227.1  4552.1   227.2  4560.9  227.19  4600.9  227.13  4622.1   227.1
  4630.9  226.98  4650.9  226.72  4660.9  226.58  4680.9  226.32  4682.1   226.3
  4700.9  226.55  4712.1   226.7  4844.9  224.54  4885.5  223.28  4890.7   223.1
  4891.7  223.06  4932.9  221.63  4938.5  221.51  4971.9  220.79  4980.9  220.76
  4993.8  220.72  4995.6   219.1  4996.8  217.74  4997.5  217.17  5000.4  217.13
  5002.2  217.14  5002.4  217.14  5003.2  217.67    5004  218.86    5006  219.26
  5009.3  221.03  5020.1   221.2  5030.4  221.37  5069.7  221.17  5081.8  221.11
  5119.2  220.91  5119.6  220.91  5143.2  220.78  5231.5   222.7  5311.5   226.2
  5331.5   227.4  5361.5   227.6  5371.5     228  5381.5     229  5401.5   229.5
  5527.2   230.1
BR U #Mann= 3
  4550.9     .06  4993.8      .1  5009.3     .06
BR U Banks=4993.8,5009.3
BR D #Sta/Elev= 46
  4550.9   227.1  4552.1   227.2  4560.9  227.19  4600.9  227.13  4622.1   227.1
  4630.9  226.98  4650.9  226.72  4660.9  226.58  4680.9  226.32  4682.1   226.3
  4700.9  226.55  4712.1   226.7  4844.9  224.54  4885.5  223.28  4890.7   223.1
  4891.7  223.06  4932.9  221.63  4938.5  221.51  4971.9  220.79  4980.9  220.76
  4993.8  220.72  4995.6   219.1  4996.8  217.74  4997.5  217.17  5000.4  217.13
  5002.2  217.14  5002.4  217.14  5003.2  217.67    5004  218.86    5006  219.26
  5009.3  221.03  5020.1   221.2  5030.4  221.37  5069.7  221.17  5081.8  221.11
  5119.2  220.91  5119.6  220.91  5143.2  220.78  5231.5   222.7  5311.5   226.2
  5331.5   227.4  5361.5   227.6  5371.5     228  5381.5     229  5401.5   229.5
  5527.2   230.1
BR D #Mann= 3
  4550.9     .06  4993.8      .1  5009.3     .06
BR D Banks=4993.8,5009.3
BC Design=,, 0 ,, 0 ,,,,,,
BC HTab HWMax=233.22

Type RM Length L Ch R = 1 ,2313.0  ,37.5,36,31.1
BEGIN DESCRIPTION:
K166-01-00-S8_PRIVATEACCESS-XS2
END DESCRIPTION:
XS GIS Cut Line= 4
      2941563.69     13938911.53       2941050.6      13938893.2
       2940754.2     13938896.41      2940369.87     13938931.19
#Sta/Elev= 30
  4331.4  233.22  4550.9  227.08  4552.1  227.18  4622.1  227.08  4682.1  226.28
  4712.1  226.68  4844.9  224.52  4885.5  223.26  4932.9  221.61  4971.9  220.77
  4993.8   220.7  4995.6  219.08  4996.8  217.72  4997.5  217.15  5000.4  217.11
  5002.4  217.12  5003.2  217.65    5004  218.84    5006  219.24  5009.3  221.01
  5030.4  221.35  5143.2  220.76  5231.5  222.68  5311.5  226.18  5331.5  227.38
  5361.5  227.58  5371.5  227.98  5381.5  228.98  5401.5  229.48  5527.2  230.08
#Mann= 4 ,-1 , 0
  4331.4     .06       0  4993.8      .1       0  5009.3     .06       0
  5527.2     .99       0
#XS Ineff= 2 , 0
       0  4989.1     219  5013.1       0     219
Permanent Ineff=
       F       F
Bank Sta=4993.8,5009.3
XS Rating Curve= 0
Exp/Cntr=.5,.3

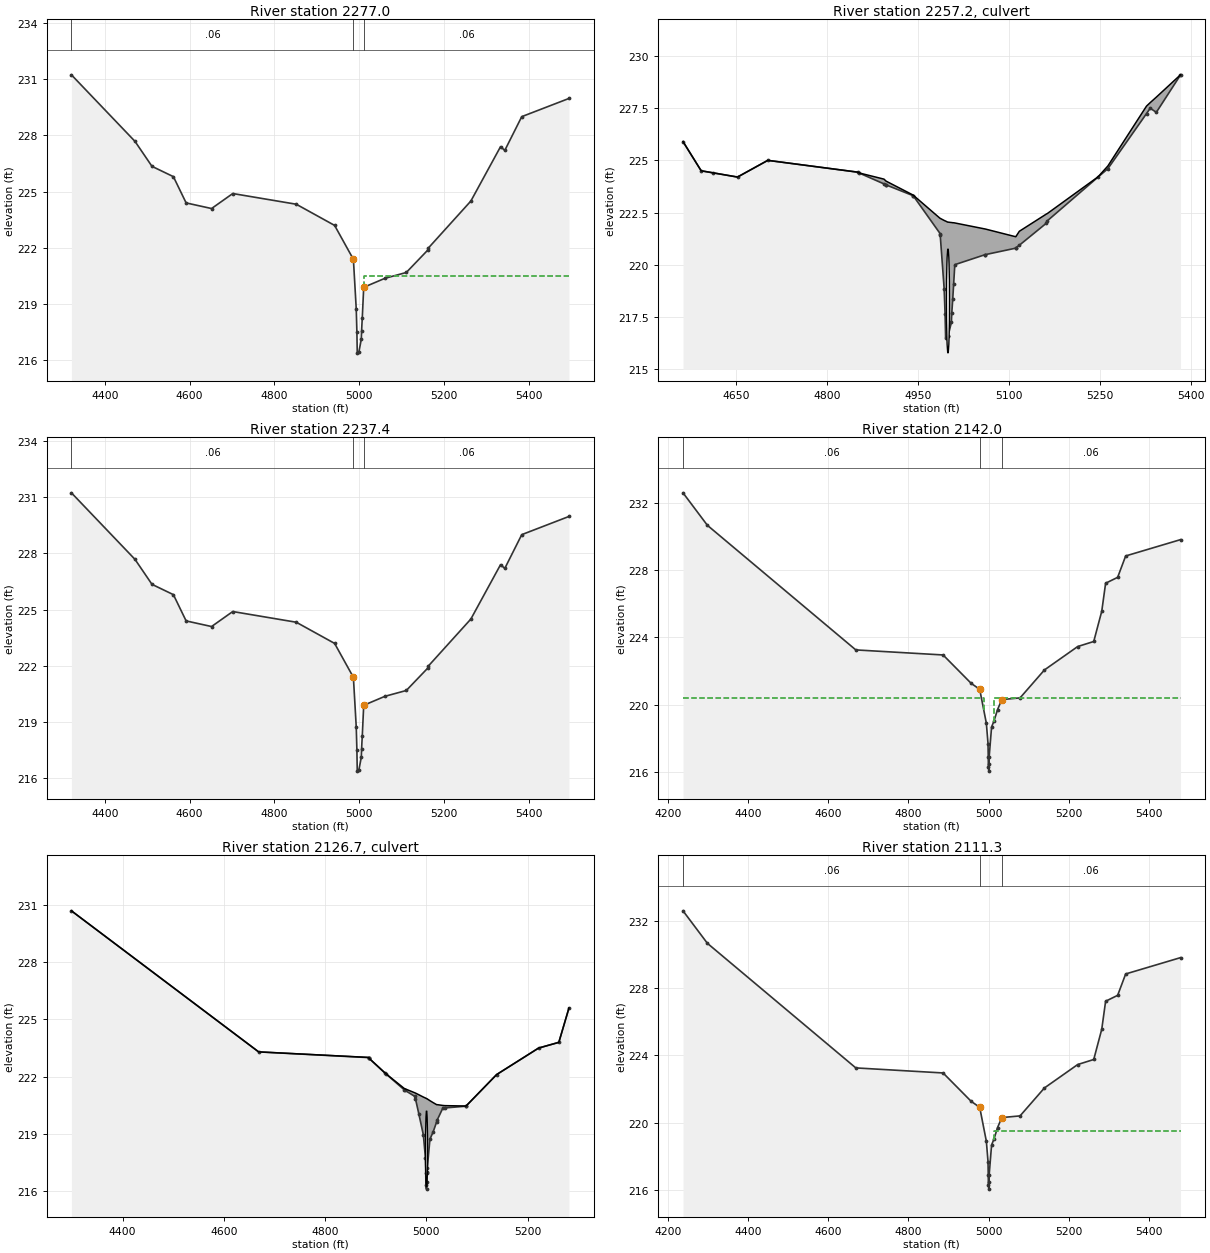
Type RM Length L Ch R = 1 ,2277.0  ,39.7,39.6,39.7
BEGIN DESCRIPTION:
K166-01-00-S7_PRIVATEACCESS-XS3
END DESCRIPTION:
XS GIS Cut Line= 4
      2941568.33     13938825.63       2941038.4     13938850.98
      2940727.89     13938868.58      2940398.79     13938907.38
#Sta/Elev= 27
  4321.3  231.23  4471.3  227.68  4511.3  226.35  4561.8   225.8  4591.8   224.4
  4651.8   224.1  4701.8   224.9  4851.5  224.33    4942   223.2  4986.3  221.39
    4993  218.74  4994.5  217.54  4995.4  216.39  4999.4  216.47  5004.9  217.13
  5005.6  217.58  5007.2  218.26  5010.6   219.9  5060.7  220.38    5111  220.69
  5161.9  221.89  5163.3     222  5263.3   224.5  5333.3   227.4  5343.3   227.2
  5383.3     229  5494.6  229.97
#Mann= 3 ,-1 , 0
  4321.3     .06       0  4986.3     .05       0  5010.6     .06       0
#XS Ineff= 2 , 0
       0  4986.8   220.5  5011.8       0   220.5
Permanent Ineff=
       F       F
Bank Sta=4986.3,5010.6
XS Rating Curve= 0
Exp/Cntr=.5,.3

Type RM Length L Ch R = 2 ,2257.2  ,,,
BEGIN DESCRIPTION:
PRIVATE ACCESS 1100' US FROM PENICK; further U/S
Structure ID: K166-01-00-S7; CMP projecting from fill VRR
END DESCRIPTION:
Bridge Culvert--1,0,-1,-1, 0
Deck Dist Width WeirC Skew NumUp NumDn MinLoCord MaxHiCord MaxSubmerge Is_Ogee
10,28.5,3,0, 38, 38, , , .95, 0, ,,,
  4561.8  4591.8  4611.8  4651.8  4701.8  4851.5  4852.2  4893.7  4896.5  4897.4
  4941.5    4942  4986.3  4986.5    4993  4994.5  4995.4  4998.8  4999.4  5004.9
  5005.6  5007.2  5008.7  5010.6  5060.7  5060.8    5111  5111.3  5117.1  5161.9
  5163.3  5247.1  5263.3  5327.1  5333.3  5343.3 5383.18  5383.3
   225.9   224.5   224.4   224.2     225  224.43   224.4   224.1  224.02     224
  223.34  223.33  222.22  222.22  222.12   222.1  222.09  222.04  222.04  222.02
  222.02  222.01  222.01     222  221.71  221.71  221.34  221.34   221.6  222.43
  222.45  224.21  224.73   227.6  227.77  228.03   229.1   229.1
   225.9   224.5   224.4   224.2     225  224.43   224.4  223.87  223.83  223.82
  223.31   223.3  221.49  221.41  218.84  217.64  216.49  216.56  216.57  217.23
  217.68  218.36  219.08     220  220.48  220.48  220.79   220.8  220.93  221.99
   222.1   224.2   224.6  227.24   227.5   227.3  229.09   229.1
  4561.8  4591.8  4611.8  4651.8  4701.8  4851.5  4852.2  4893.7  4896.5  4897.4
  4941.5    4942  4986.3  4986.5    4993  4994.5  4995.4  4998.8  4999.4  5004.9
  5005.6  5007.2  5008.7  5010.6  5060.7  5060.8    5111  5111.3  5117.1  5161.9
  5163.3  5247.1  5263.3  5327.1  5333.3  5343.3 5383.18  5383.3
   225.9   224.5   224.4   224.2     225  224.43   224.4   224.1  224.02     224
  223.34  223.33  222.22  222.22  222.12   222.1  222.09  222.04  222.04  222.02
  222.02  222.01  222.01     222  221.71  221.71  221.34  221.34   221.6  222.43
  222.45  224.21  224.73   227.6  227.77  228.03   229.1   229.1
  225.21  223.81  223.71  223.51  224.31  223.74  223.71  223.18  223.14  223.13
  222.62  222.61   220.8  220.72  218.15  216.95   215.8  215.87  215.88  216.54
  216.99  217.67  218.39  219.31  219.79  219.79   220.1  220.11  220.24   221.3
  221.41  223.51  223.91  226.55  226.81  226.61   228.4  228.41
BR Coef= 1 , 0 , 0 ,1.25, 0 ,,,.8,-1,2,0,
WSPro=,,,, 1 ,,,, 0 ,,,, 0 ,,,,-1 ,-1 ,-1 , 0 , 0 , 0 , 0 , 0
Culvert=1,5,,28.5,.026,.9,1,2,3,215.76,4999.3,215.93,4999.3,Culvert #1  , 0 ,10
Culvert Bottom n=.026
BR U #Sta/Elev= 38
  4561.8   225.9  4591.8   224.5  4611.8   224.4  4651.8   224.2  4701.8     225
  4851.5  224.43  4852.2   224.4  4893.7  223.87  4896.5  223.83  4897.4  223.82
  4941.5  223.31    4942   223.3  4986.3  221.49  4986.5  221.41    4993  218.84
  4994.5  217.64  4995.4  216.49  4998.8  216.56  4999.4  216.57  5004.9  217.23
  5005.6  217.68  5007.2  218.36  5008.7  219.08  5010.6     220  5060.7  220.48
  5060.8  220.48    5111  220.79  5111.3   220.8  5117.1  220.93  5161.9  221.99
  5163.3   222.1  5247.1   224.2  5263.3   224.6  5327.1  227.24  5333.3   227.5
  5343.3   227.3 5383.18  229.09  5383.3   229.1
BR U #Mann= 3
  4561.8     .06  4986.3     .05  5010.6     .06
BR U Banks=4986.3,5010.6
BR D #Sta/Elev= 38
  4561.8   225.9  4591.8   224.5  4611.8   224.4  4651.8   224.2  4701.8     225
  4851.5  224.43  4852.2   224.4  4893.7  223.87  4896.5  223.83  4897.4  223.82
  4941.5  223.31    4942   223.3  4986.3  221.49  4986.5  221.41    4993  218.84
  4994.5  217.64  4995.4  216.49  4998.8  216.56  4999.4  216.57  5004.9  217.23
  5005.6  217.68  5007.2  218.36  5008.7  219.08  5010.6     220  5060.7  220.48
  5060.8  220.48    5111  220.79  5111.3   220.8  5117.1  220.93  5161.9  221.99
  5163.3   222.1  5247.1   224.2  5263.3   224.6  5327.1  227.24  5333.3   227.5
  5343.3   227.3 5383.18  229.09  5383.3   229.1
BR D #Mann= 3
  4561.8     .06  4986.3     .05  5010.6     .06
BR D Banks=4986.3,5010.6
BC Design=,, 0 ,, 0 ,,,,,,
BC HTab HWMax=231.23

Type RM Length L Ch R = 1 ,2237.4  ,101.3,95.4,82.9
BEGIN DESCRIPTION:
K166-01-00-S7_PRIVATEACCESS-XS2
END DESCRIPTION:
XS GIS Cut Line= 4
      2941564.36     13938786.19      2941034.41     13938811.55
      2940723.72     13938829.16      2940394.47     13938867.98
#Sta/Elev= 27
  4321.3  231.23  4471.3  227.68  4511.3  226.35  4561.8   225.8  4591.8   224.4
  4651.8   224.1  4701.8   224.9  4851.5  224.33    4942   223.2  4986.3  221.39
    4993  218.74  4994.5  217.54  4995.4  216.39  4999.4  216.47  5004.9  217.13
  5005.6  217.58  5007.2  218.26  5010.6   219.9  5060.7  220.38    5111  220.69
  5161.9  221.89  5163.3     222  5263.3   224.5  5333.3   227.4  5343.3   227.2
  5383.3     229  5494.6  229.97
#Mann= 3 ,-1 , 0
  4321.3     .06       0  4986.3     .05       0  5010.6     .06       0
#XS Ineff= 2 , 0
       0  4986.8   218.5  5011.8       0   218.5
Permanent Ineff=
       F       F
Bank Sta=4986.3,5010.6
XS Rating Curve= 0
Exp/Cntr=.5,.3

Type RM Length L Ch R = 1 ,2142.0  ,31.8,30.7,32
BEGIN DESCRIPTION:
K166-01-00-S6_PRIVATEACCESS-XS3
END DESCRIPTION:
XS GIS Cut Line= 4
      2941622.14     13938620.29      2940979.81     13938703.62
      2940788.43     13938743.45       2940400.3     13938826.05
#Sta/Elev= 26
  4237.9  232.59  4298.7  230.66  4668.7  223.26  4886.3  222.96  4956.5  221.27
  4977.6  220.92  4994.2   218.9  4998.3   217.7  4998.9   216.9  4999.3  216.28
  5000.4  216.06  5000.8  216.46  5001.1  216.88  5007.2  218.68  5013.4  219.05
    5022  219.71  5032.7  220.31  5078.2  220.41    5139  222.07  5221.9  223.46
  5261.9  223.76  5281.9  225.56  5291.5  227.22  5321.5  227.57  5341.5  228.84
  5478.3  229.81
#Mann= 3 ,-1 , 0
  4237.9     .06       0  4977.6     .05       0  5032.7     .06       0
#XS Ineff= 2 , 0
       0  4988.5   220.4  5012.5       0   220.4
Permanent Ineff=
       F       F
Bank Sta=4977.6,5032.7
XS Rating Curve= 0
Exp/Cntr=.5,.3

Type RM Length L Ch R = 2 ,2126.7  ,,,
BEGIN DESCRIPTION:
PRIVATE ACCESS 1100' US FROM PENICK
Structure ID: K166-01-00-S6
END DESCRIPTION:
Bridge Culvert--1,0,-1,-1, 0
Deck Dist Width WeirC Skew NumUp NumDn MinLoCord MaxHiCord MaxSubmerge Is_Ogee
10,10.7,3,0, 33, 33, , , .95, 0, ,,,
  4298.7  4668.7  4886.2  4886.3  4886.4  4919.1  4920.9  4956.5  4957.4  4977.6
  4978.5  4985.3  4994.2  4998.3  4998.9  4999.3  5000.4  5000.8  5001.1  5001.3
    5002  5007.2  5013.4  5020.5    5022  5032.7    5037  5078.2  5078.6    5139
  5221.9  5261.9  5281.9
   230.7   223.3  223.01  223.01  222.98  222.18  222.14  221.38  221.37  221.15
  221.14  221.05  220.93  220.88  220.87  220.87  220.85  220.85  220.84  220.84
  220.83  220.74  220.64  220.53  220.53  220.49  220.48  220.46  220.46  222.11
   223.5   223.8   225.6
   230.7   223.3     223     223  222.97  222.17  222.13  221.31  221.29  220.96
  220.85  220.04  218.94  217.74  216.94  216.32   216.1   216.5  216.92  216.99
  217.22  218.72  219.09  219.63  219.75  220.35  220.36  220.45  220.46  222.11
   223.5   223.8   225.6
  4298.7  4668.7  4886.2  4886.3  4886.4  4919.1  4920.9  4956.5  4957.4  4977.6
  4978.5  4985.3  4994.2  4998.3  4998.9  4999.3  5000.4  5000.8  5001.1  5001.3
    5002  5007.2  5013.4  5020.5    5022  5032.7    5037  5078.2  5078.6    5139
  5221.9  5261.9  5281.9
   230.7   223.3  223.01  223.01  222.98  222.18  222.14  221.38  221.37  221.15
  221.14  221.05  220.93  220.88  220.87  220.87  220.85  220.85  220.84  220.84
  220.83  220.74  220.64  220.53  220.53  220.49  220.48  220.46  220.46  222.11
   223.5   223.8   225.6
   230.7   223.3     223     223  222.97  222.17  222.13  221.31  221.29  220.96
  220.85  220.04  218.94  217.74  216.94  216.32   216.1   216.5  216.92  216.99
  217.22  218.72  219.09  219.63  219.75  220.35  220.36  220.45  220.46  222.11
   223.5   223.8   225.6
BR Coef= 1 , 0 , 0 ,1.25, 0 ,,,.8,-1,2,0,
WSPro=,,,, 1 ,,,, 0 ,,,, 0 ,,,,-1 ,-1 ,-1 , 0 , 0 , 0 , 0 , 0
Culvert=1,4,,10.7,.026,.9,1,2,3,216.21,5000.5,216.04,5000.5,Culvert #1  , 0 ,10
Culvert Bottom n=.026
BR U #Sta/Elev= 33
  4298.7   230.7  4668.7   223.3  4886.2     223  4886.3     223  4886.4  222.97
  4919.1  222.17  4920.9  222.13  4956.5  221.31  4957.4  221.29  4977.6  220.96
  4978.5  220.85  4985.3  220.04  4994.2  218.94  4998.3  217.74  4998.9  216.94
  4999.3  216.32  5000.4   216.1  5000.8   216.5  5001.1  216.92  5001.3  216.99
    5002  217.22  5007.2  218.72  5013.4  219.09  5020.5  219.63    5022  219.75
  5032.7  220.35    5037  220.36  5078.2  220.45  5078.6  220.46    5139  222.11
  5221.9   223.5  5261.9   223.8  5281.9   225.6
BR U #Mann= 3
  4298.7     .06  4977.6     .05  5032.7     .06
BR U Banks=4977.6,5032.7
BR D #Sta/Elev= 33
  4298.7   230.7  4668.7   223.3  4886.2     223  4886.3     223  4886.4  222.97
  4919.1  222.17  4920.9  222.13  4956.5  221.31  4957.4  221.29  4977.6  220.96
  4978.5  220.85  4985.3  220.04  4994.2  218.94  4998.3  217.74  4998.9  216.94
  4999.3  216.32  5000.4   216.1  5000.8   216.5  5001.1  216.92  5001.3  216.99
    5002  217.22  5007.2  218.72  5013.4  219.09  5020.5  219.63    5022  219.75
  5032.7  220.35    5037  220.36  5078.2  220.45  5078.6  220.46    5139  222.11
  5221.9   223.5  5261.9   223.8  5281.9   225.6
BR D #Mann= 3
  4298.7     .06  4977.6     .05  5032.7     .06
BR D Banks=4977.6,5032.7
BC Design=,, 0 ,, 0 ,,,,,,
BC HTab HWMax=232.59

Type RM Length L Ch R = 1 ,2111.3  ,154.4,158.9,165.5
BEGIN DESCRIPTION:
K166-01-00-S6_PRIVATEACCESS-XS2
END DESCRIPTION:
XS GIS Cut Line= 4
      2941613.69     13938590.08      2940971.17     13938673.43
       2940779.6     13938713.31      2940391.45      13938795.9
#Sta/Elev= 26
  4237.9  232.59  4298.7  230.66  4668.7  223.26  4886.3  222.96  4956.5  221.27
  4977.6  220.92  4994.2   218.9  4998.3   217.7  4998.9   216.9  4999.3  216.28
  5000.4  216.06  5000.8  216.46  5001.1  216.88  5007.2  218.68  5013.4  219.05
    5022  219.71  5032.7  220.31  5078.2  220.41    5139  222.07  5221.9  223.46
  5261.9  223.76  5281.9  225.56  5291.5  227.22  5321.5  227.57  5341.5  228.84
  5478.3  229.81
#Mann= 3 ,-1 , 0
  4237.9     .06       0  4977.6     .05       0  5032.7     .06       0
#XS Ineff= 2 , 0
       0  4988.5   219.5  5012.5       0   219.5
Permanent Ineff=
       F       F
Bank Sta=4977.6,5032.7
XS Rating Curve= 0
Exp/Cntr=.5,.3