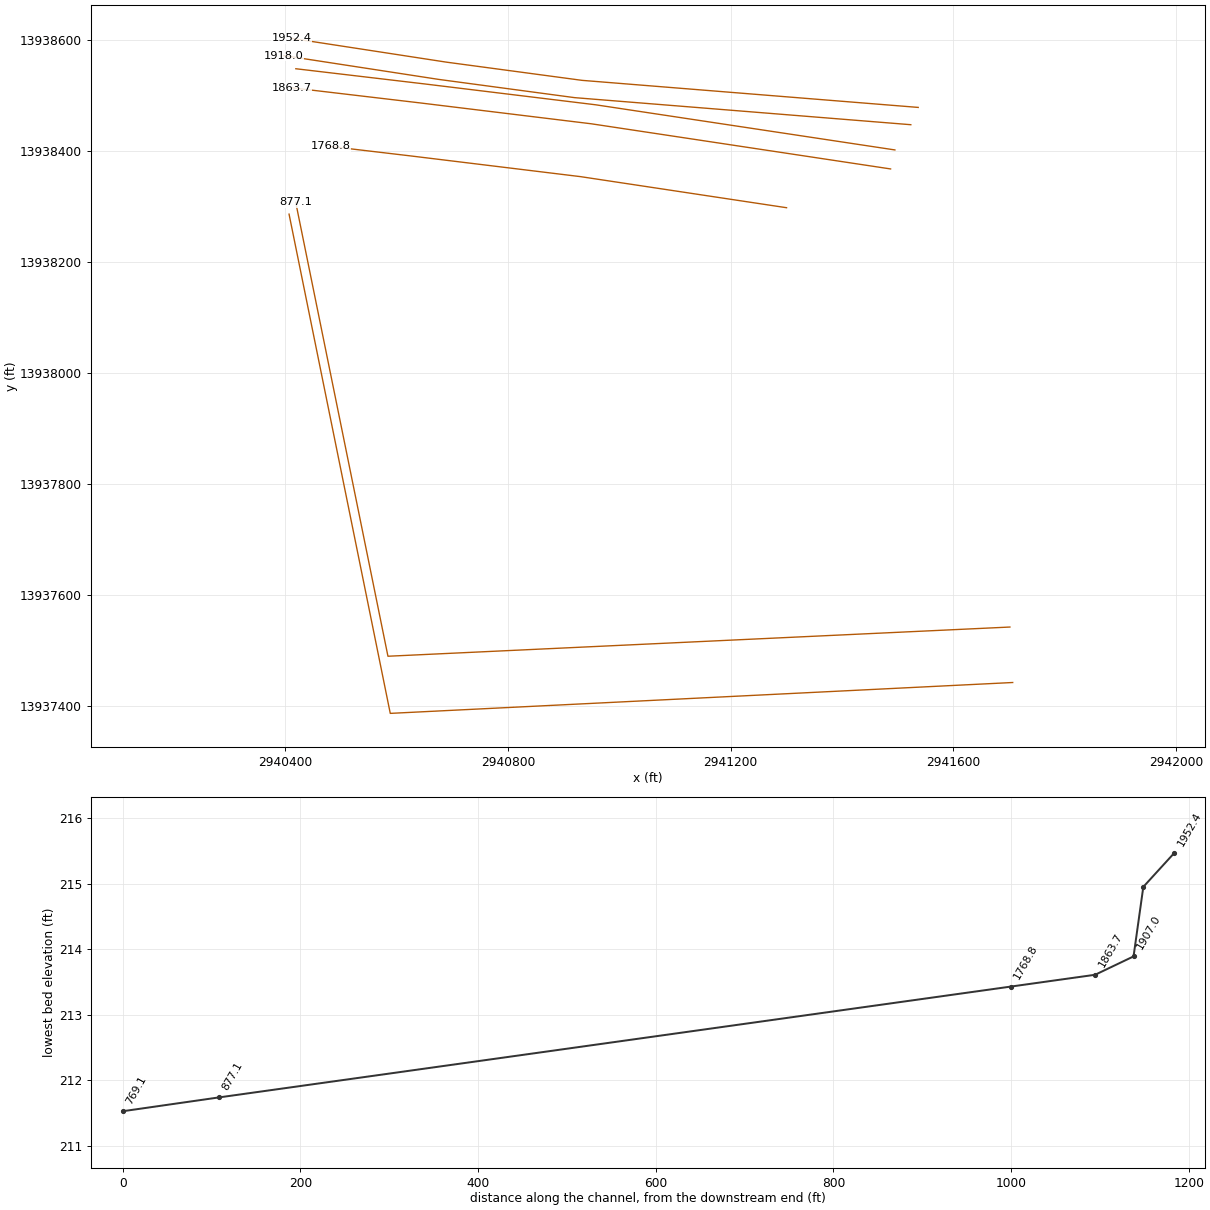
HEC-RAS study K166-01-00.prj: K166-01-00

--- K166-01-00.g01 (geometry) --- (continued)

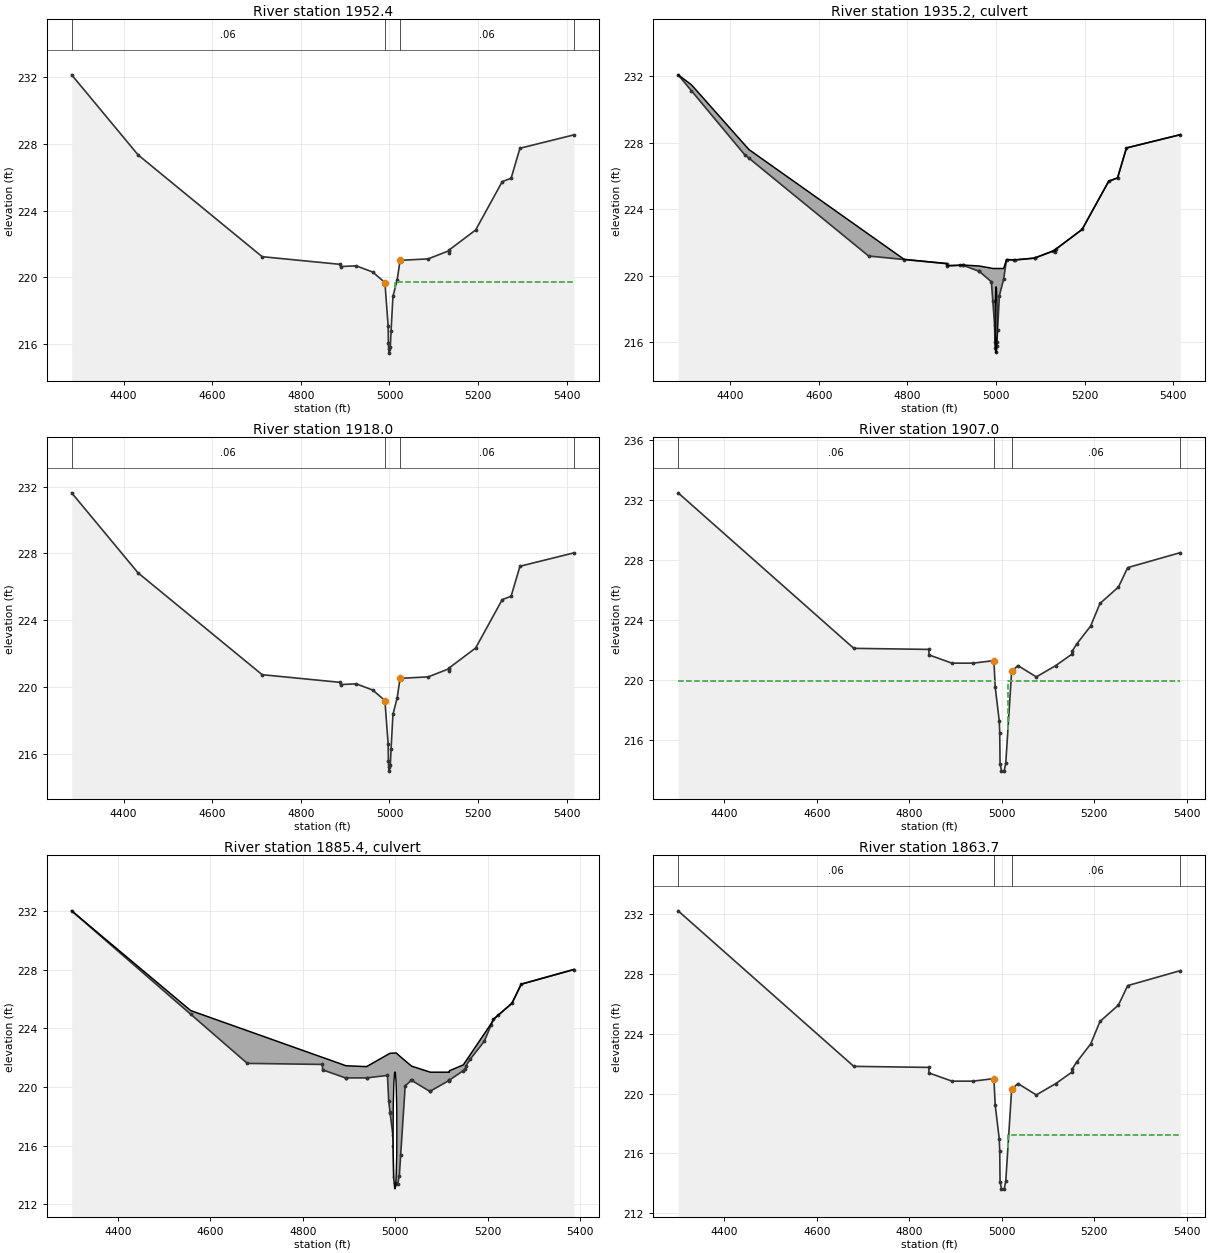
Type RM Length L Ch R = 1 ,1952.4  ,32.6,34.4,35.1
BEGIN DESCRIPTION:
K166-01-00-S5_PRIVATEDR-XS3
END DESCRIPTION:
XS GIS Cut Line= 4
      2941537.05     13938478.67      2940933.08     13938527.39
      2940689.39     13938560.17      2940411.04     13938603.05
#Sta/Elev= 26
  4282.7  232.14  4432.7  227.34  4712.7  221.24  4889.1  220.78  4889.5  220.65
    4925  220.69  4962.3  220.32  4989.7  219.69    4997  217.09  4997.6  216.05
  4998.2   215.7  4999.8  215.46  5001.9  215.83  5003.6  216.78  5007.8  218.86
  5017.4  219.85  5023.9  221.02  5087.4  221.11  5133.7  221.59  5134.2  221.49
  5134.5  221.64  5194.5  222.84  5254.5  225.74  5274.5  225.94  5294.5  227.74
  5416.1  228.54
#Mann= 4 ,-1 , 0
  4282.7     .06       0  4989.7     .08       0  5023.9     .06       0
  5416.1     .99       0
#XS Ineff= 2 , 0
       0  4988.4   219.7  5012.4       0   219.7
Permanent Ineff=
       F       F
Bank Sta=4989.7,5023.9
XS Rating Curve= 0
Exp/Cntr=.5,.3

Type RM Length L Ch R = 2 ,1935.2  ,,,
BEGIN DESCRIPTION:
PRIVATE DRIVE 775' US PENICK
Structure ID: K166-01-00-S5
It is not clear what type of pipe is underneath the road from the photos and not specified in survey points file.  Assumed CMP projecting from fill. - JJA 3/26/03
END DESCRIPTION:
Bridge Culvert--1,0,-1,-1, 0
Deck Dist Width WeirC Skew NumUp NumDn MinLoCord MaxHiCord MaxSubmerge Is_Ogee
10,24,3,0, 38, 38, , , .95, 0, ,,,
  4282.7  4312.8  4432.7  4442.8  4712.7  4792.8  4889.1  4889.5  4919.6  4924.7
    4925  4962.2  4962.3  4989.7    4993    4997  4997.6  4998.2  4999.8  5001.9
  5002.3  5003.6  5007.8  5017.4  5023.9  5040.6  5042.4  5087.4  5087.9  5128.3
  5133.7  5134.2  5134.5  5194.5  5254.5  5274.5  5294.5  5416.1
   232.1   231.5   227.9   227.6  222.51     221  220.75  220.62  220.65  220.66
  220.66   220.6   220.6  220.47  220.45  220.45  220.45  220.45  220.45  220.45
  220.45  220.45  220.45  220.45  220.99  220.97  220.97  221.08  221.09   221.5
  221.55  221.45   221.6   222.8   225.7   225.9   227.7   228.5
                                          220.99  220.74  220.61  220.64  220.65
  220.65  220.28  220.28  219.65  218.47  217.05  216.01  215.66  215.42  215.79
  216.05  216.74  218.82  219.81  220.98  220.96  220.96  221.07  221.08  221.49
  221.55  221.45   221.6   222.8   225.7   225.9   227.7   228.5
  4282.7  4312.8  4432.7  4442.8  4712.7  4792.8  4889.1  4889.5  4919.6  4924.7
    4925  4962.2  4962.3  4989.7    4993    4997  4997.6  4998.2  4999.8  5001.9
  5002.3  5003.6  5007.8  5017.4  5023.9  5040.6  5042.4  5087.4  5087.9  5128.3
  5133.7  5134.2  5134.5  5194.5  5254.5  5274.5  5294.5  5416.1
   232.1   231.5   227.9   227.6  222.51     221  220.75  220.62  220.65  220.66
  220.66   220.6   220.6  220.47  220.45  220.45  220.45  220.45  220.45  220.45
  220.45  220.45  220.45  220.45  220.99  220.97  220.97  221.08  221.09   221.5
  221.55  221.45   221.6   222.8   225.7   225.9   227.7   228.5
                                                  220.74  220.61  220.64  220.65
  220.65  220.28  220.28  219.65  218.47  217.05  216.01  215.66  215.42  215.79
  216.05  216.74  218.82  219.81  220.98  220.96  220.96  221.07  221.08  221.49
  221.55  221.45   221.6   222.8   225.7   225.9   227.7   228.5
BR Coef= 1 , 0 , 0 ,1.25, 0 ,,,.8,-1,2,0,
WSPro=,,,, 1 ,,,, 0 ,,,, 0 ,,,,-1 ,-1 ,-1 , 0 , 0 , 0 , 0 , 0
Culvert=1,4,,24,.026,.9,1,2,3,215.36,5000.4,214.94,5000.4,Culvert #1  , 0 ,10
Culvert Bottom n=.026
BR U #Sta/Elev= 38
  4282.7   232.1  4312.8  231.14  4432.7   227.3  4442.8  227.08  4712.7   221.2
  4792.8  220.99  4889.1  220.74  4889.5  220.61  4919.6  220.64  4924.7  220.65
    4925  220.65  4962.2  220.28  4962.3  220.28  4989.7  219.65    4993  218.47
    4997  217.05  4997.6  216.01  4998.2  215.66  4999.8  215.42  5001.9  215.79
  5002.3  216.05  5003.6  216.74  5007.8  218.82  5017.4  219.81  5023.9  220.98
  5040.6  220.96  5042.4  220.96  5087.4  221.07  5087.9  221.08  5128.3  221.49
  5133.7  221.55  5134.2  221.45  5134.5   221.6  5194.5   222.8  5254.5   225.7
  5274.5   225.9  5294.5   227.7  5416.1   228.5
BR U #Mann= 3
  4282.7     .06  4989.7     .08  5023.9     .06
BR U Banks=4989.7,5023.9
BR D #Sta/Elev= 38
  4282.7   232.1  4312.8  231.14  4432.7   227.3  4442.8  227.08  4712.7   221.2
  4792.8  220.99  4889.1  220.74  4889.5  220.61  4919.6  220.64  4924.7  220.65
    4925  220.65  4962.2  220.28  4962.3  220.28  4989.7  219.65    4993  218.47
    4997  217.05  4997.6  216.01  4998.2  215.66  4999.8  215.42  5001.9  215.79
  5002.3  216.05  5003.6  216.74  5007.8  218.82  5017.4  219.81  5023.9  220.98
  5040.6  220.96  5042.4  220.96  5087.4  221.07  5087.9  221.08  5128.3  221.49
  5133.7  221.55  5134.2  221.45  5134.5   221.6  5194.5   222.8  5254.5   225.7
  5274.5   225.9  5294.5   227.7  5416.1   228.5
BR D #Mann= 3
  4282.7     .06  4989.7     .08  5023.9     .06
BR D Banks=4989.7,5023.9
BC Design=,, 0 ,, 0 ,,,,,,
BC HTab HWMax=232.14

Type RM Length L Ch R = 1 ,1918.0  ,8.5,11,11.1
BEGIN DESCRIPTION:
K166-01-00-S5_PRIVATEDR-XS2
END DESCRIPTION:
XS GIS Cut Line= 4
      2941523.77     13938447.53      2940919.67     13938496.27
       2940675.8     13938529.07       2940397.4     13938571.96
#Sta/Elev= 26
  4282.7  231.63  4432.7  226.83  4712.7  220.73  4889.1  220.27  4889.5  220.14
    4925  220.18  4962.3  219.81  4989.7  219.18    4997  216.58  4997.6  215.54
  4998.2  215.19  4999.8  214.95  5001.9  215.32  5003.6  216.27  5007.8  218.35
  5017.4  219.34  5023.9  220.51  5087.4   220.6  5133.7  221.08  5134.2  220.98
  5134.5  221.13  5194.5  222.33  5254.5  225.23  5274.5  225.43  5294.5  227.23
  5416.1  228.03
#Mann= 4 ,-1 , 0
  4282.7     .06       0  4989.7     .08       0  5023.9     .06       0
  5416.1     .99       0
#XS Ineff= 2 , 0
       0  4988.4     217  5012.4       0     217
Permanent Ineff=
       F       F
Bank Sta=4989.7,5023.9
XS Rating Curve= 0
Exp/Cntr=.5,.3

Type RM Length L Ch R = 1 ,1907.0  ,34.9,43.3,37.7
BEGIN DESCRIPTION:
K166-01-00-S4_PRIVATEDR-XS3
END DESCRIPTION:
XS GIS Cut Line= 4
       2941495.2      13938402.1      2940957.35     13938483.42
      2940651.09     13938520.84      2940418.86      13938548.3
#Sta/Elev= 26
  4300.1   232.5  4680.1   222.1  4842.5  222.03  4842.8  221.66  4892.5  221.11
    4938  221.11  4983.2  221.28    4986  219.51  4994.8  217.24  4995.8  216.47
  4996.5  214.39  4999.5  213.92  5005.4  213.89  5008.9  214.44  5021.6  220.57
  5035.2  220.95  5074.9  220.19  5117.1  220.95  5151.8  221.71    5153  221.94
  5162.6   222.4  5192.6   223.6  5212.6   225.1  5252.6   226.2  5272.6   227.5
  5386.4   228.5
#Mann= 4 ,-1 , 0
  4300.1     .06       0  4983.2     .06       0  5021.6     .06       0
  5386.4     .99       0
#XS Ineff= 2 , 0
       0  4985.5   219.9  5013.5       0   219.9
Permanent Ineff=
       F       F
Bank Sta=4983.2,5021.6
XS Rating Curve= 0
Exp/Cntr=.5,.3

Type RM Length L Ch R = 2 ,1885.4  ,,,
BEGIN DESCRIPTION:
PRIVATE DRIVE 730' US PENICK
Structure ID: K166-01-00-S4
Pipe is not corrugated metal, but some other metal type. -JJA 3/16/03
END DESCRIPTION:
Bridge Culvert--1,0,-1,-1, 0
Deck Dist Width WeirC Skew NumUp NumDn MinLoCord MaxHiCord MaxSubmerge Is_Ogee
10,27,3,0, 40, 40, , , .95, 0, ,,,
  4300.1  4557.6  4680.1  4842.5  4842.8  4892.5  4893.3  4937.9    4938  4983.2
    4986  4988.6  4989.1  4994.8  4995.8  4996.5  4999.5  5001.9  5005.4  5008.9
  5011.9  5021.6  5035.2  5035.7  5074.9  5076.2  5115.6  5117.1  5117.4  5147.4
  5151.8    5153  5162.6  5192.6  5207.4  5212.6  5223.1  5252.6  5272.6  5386.4
     232   225.2  223.83  222.01  222.01  221.45  221.44  221.38  221.38  222.19
  222.24  222.29  222.29   222.3   222.3   222.3  222.31  222.31  222.22  222.12
  222.04  221.78  221.42  221.41  221.01     221     221     221   221.1   221.5
  221.71  221.76  222.21  223.61   224.3  224.61   224.9   225.7     227     228
     232  224.95   221.6  221.53  221.16  220.61  220.61  220.61  220.61  220.78
  219.01  218.32  218.19  216.74  215.97  213.89  213.42  213.41  213.39  213.94
  215.39  220.07  220.45  220.44  219.69  219.71  220.42  220.45  220.46  221.11
  221.21  221.44   221.9   223.1  224.21   224.6  224.89   225.7     227     228
  4300.1  4557.6  4680.1  4842.5  4842.8  4892.5  4893.3  4937.9    4938  4983.2
    4986  4988.6  4989.1  4994.8  4995.8  4996.5  4999.5  5001.9  5005.4  5008.9
  5011.9  5021.6  5035.2  5035.7  5074.9  5076.2  5115.6  5117.1  5117.4  5147.4
  5151.8    5153  5162.6  5192.6  5207.4  5212.6  5223.1  5252.6  5272.6  5386.4
     232   225.2  223.83  222.01  222.01  221.45  221.44  221.38  221.38  222.19
  222.24  222.29  222.29   222.3   222.3   222.3  222.31  222.31  222.22  222.12
  222.04  221.78  221.42  221.41  221.01     221     221     221   221.1   221.5
  221.71  221.76  222.21  223.61   224.3  224.61   224.9   225.7     227     228
     232  224.95   221.6  221.53  221.16  220.61  220.61  220.61  220.61  220.78
  219.01  218.32  218.19  216.74  215.97  213.89  213.42  213.41  213.39  213.94
  215.39  220.07  220.45  220.44  219.69  219.71  220.42  220.45  220.46  221.11
  221.21  221.44   221.9   223.1  224.21   224.6  224.89   225.7     227     228
BR Coef= 1 , 0 , 0 ,1.25, 0 ,,,.8,-1,2,0,
WSPro=,,,, 1 ,,,, 0 ,,,, 0 ,,,,-1 ,-1 ,-1 , 0 , 0 , 0 , 0 , 0
Culvert=1,8,,27,.017,.9,1,2,3,213.03,4999.5,213.21,4999.5,Culvert #1  , 0 ,10
Culvert Bottom n=.017
BR U #Sta/Elev= 40
  4300.1     232  4557.6  224.95  4680.1   221.6  4842.5  221.53  4842.8  221.16
  4892.5  220.61  4893.3  220.61  4937.9  220.61    4938  220.61  4983.2  220.78
    4986  219.01  4988.6  218.32  4989.1  218.19  4994.8  216.74  4995.8  215.97
  4996.5  213.89  4999.5  213.42  5001.9  213.41  5005.4  213.39  5008.9  213.94
  5011.9  215.39  5021.6  220.07  5035.2  220.45  5035.7  220.44  5074.9  219.69
  5076.2  219.71  5115.6  220.42  5117.1  220.45  5117.4  220.46  5147.4  221.11
  5151.8  221.21    5153  221.44  5162.6   221.9  5192.6   223.1  5207.4  224.21
  5212.6   224.6  5223.1  224.89  5252.6   225.7  5272.6     227  5386.4     228
BR U #Mann= 3
  4300.1     .06  4983.2     .06  5021.6     .06
BR U Banks=4983.2,5021.6
BR D #Sta/Elev= 40
  4300.1  232.24  4557.6  225.19  4680.1  221.84  4842.5  221.77  4842.8   221.4
  4892.5  220.85  4893.3  220.85  4937.9  220.85    4938  220.85  4983.2  221.02
    4986  219.25  4988.6  218.56  4989.1  218.43  4994.8  216.98  4995.8  216.21
  4996.5  214.13  4999.5  213.66  5001.9  213.65  5005.4  213.63  5008.9  214.18
  5011.9  215.63  5021.6  220.31  5035.2  220.69  5035.7  220.68  5074.9  219.93
  5076.2  219.95  5115.6  220.66  5117.1  220.69  5117.4   220.7  5147.4  221.35
  5151.8  221.45    5153  221.68  5162.6  222.14  5192.6  223.34  5207.4  224.45
  5212.6  224.84  5223.1  225.13  5252.6  225.94  5272.6  227.24  5386.4  228.24
BR D #Mann= 3
  4300.1     .06  4983.2     .06  5021.6     .06
BR D Banks=4983.2,5021.6
BC Design=,, 0 ,, 0 ,,,,,,
BC HTab HWMax=232.5

Type RM Length L Ch R = 1 ,1863.7  ,96.8,94.9,99.6
BEGIN DESCRIPTION:
K166-01-00-S4_PRIVATEDR-XS2
END DESCRIPTION:
XS GIS Cut Line= 4
      2941487.42     13938367.89      2940949.64     13938449.19
      2940643.47     13938486.61      2940411.25     13938514.06
#Sta/Elev= 26
  4300.1  232.22  4680.1  221.82  4842.5  221.75  4842.8  221.38  4892.5  220.83
    4938  220.83  4983.2     221    4986  219.23  4994.8  216.96  4995.8  216.19
  4996.5  214.11  4999.5  213.64  5005.4  213.61  5008.9  214.16  5021.6  220.29
  5035.2  220.67  5074.9  219.91  5117.1  220.67  5151.8  221.43    5153  221.66
  5162.6  222.12  5192.6  223.32  5212.6  224.82  5252.6  225.92  5272.6  227.22
  5386.4  228.22
#Mann= 4 ,-1 , 0
  4300.1     .06       0  4983.2     .06       0  5021.6     .06       0
  5386.4     .99       0
#XS Ineff= 2 , 0
       0  4985.5  217.21  5013.5       0  217.21
Permanent Ineff=
       F       F
Bank Sta=4983.2,5021.6
XS Rating Curve= 0
Exp/Cntr=.5,.3

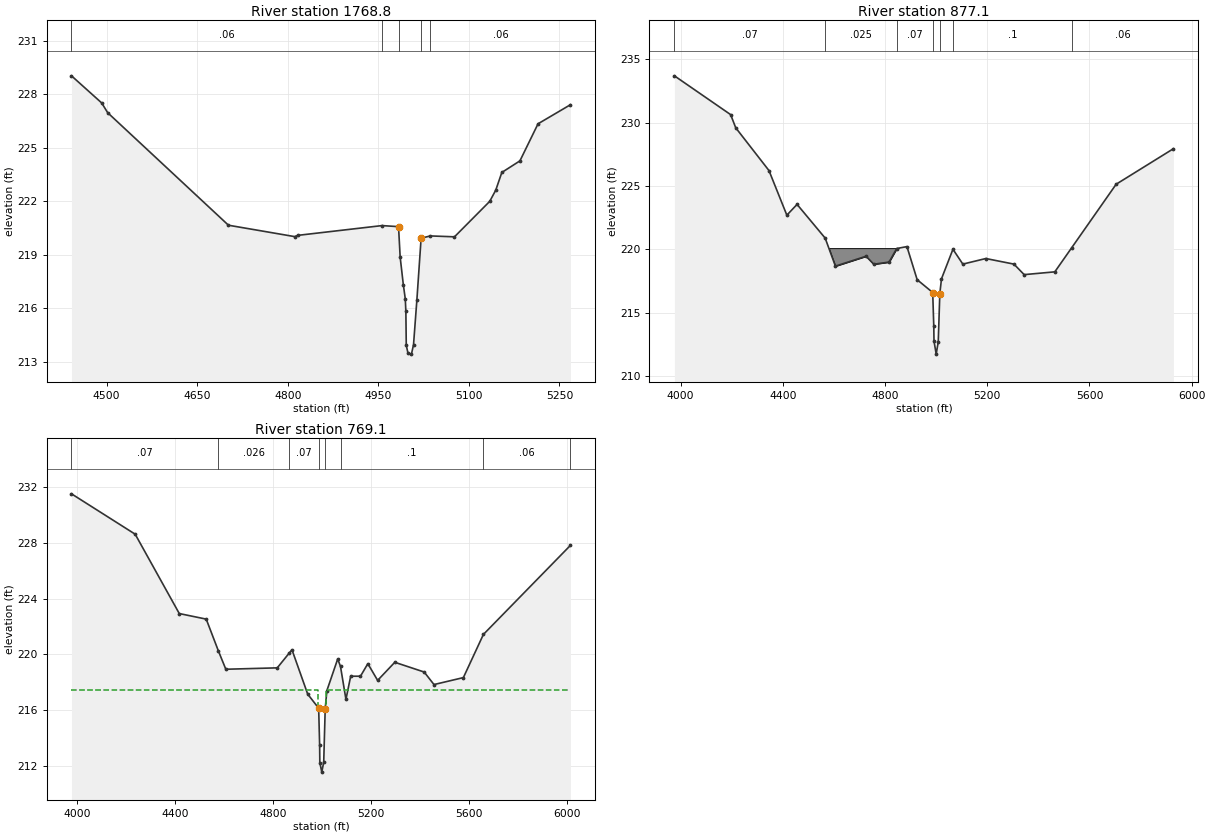
Type RM Length L Ch R = 1 ,1768.8  ,878,891.7,896.2
BEGIN DESCRIPTION:
K166-01-00-S4_PRIVATEDR-XS1
LIDAR overbanks, interpolated channel
END DESCRIPTION:
XS GIS Cut Line= 4
      2941300.51     13938298.07      2940930.34     13938354.03
      2940624.16     13938391.45      2940481.44     13938408.33
#Sta/Elev= 26
  4441.8  229.04  4491.8  227.52  4501.8  226.97  4701.8  220.66  4811.8  220.02
  4816.2  220.09  4956.2  220.64 4983.53  220.58 4986.22  218.87 4991.44  217.33
  4994.7  216.53 4995.66  215.83 4996.34  213.92 4999.22  213.48 5004.91  213.43
 5008.36  213.96 5013.95  216.49 5020.92  219.93  5036.2  220.06  5076.2  220.01
  5134.6     222  5144.6  222.63  5154.6  223.62  5184.6  224.27  5214.6  226.35
  5268.3  227.42
#Mann= 5 ,-1 , 0
  4441.8     .06       0  4956.2     .07       0 4983.53     .06       0
 5020.92     .07       0  5036.2     .06       0
Bank Sta=4983.53,5020.92
XS Rating Curve= 0
Exp/Cntr=.3,.1

Type RM Length L Ch R = 1 ,877.1   ,102.7,108,102.8
BEGIN DESCRIPTION:
K166-01-00-S3_CHARTERLN-XS4
LIDAR overbanks, interpolated channel
END DESCRIPTION:
XS GIS Cut Line= 3
      2941701.83     13937543.07      2940584.35     13937490.48
      2940418.61     13938307.82
#Sta/Elev= 30
  3975.8  233.69  4195.8  230.63  4215.8  229.59  4345.8  226.22  4415.8   222.7
  4455.8  223.55  4565.8  220.89  4605.8  218.68  4725.8  219.46  4755.8  218.83
  4815.8     219  4845.8  220.07  4885.8  220.22  4925.8  217.61 4986.62   216.6
 4990.81  213.94 4991.67  212.77 5000.26  211.74 5008.29  212.71 5014.48  216.51
 5020.95  217.68  5065.8  220.01  5104.5  218.84  5194.5  219.28  5304.5  218.84
  5344.5  218.01  5464.5  218.23    5530 220.116  5704.5  225.14  5928.5  227.94
#Mann= 7 ,-1 , 0
  3975.8     .07       0  4565.8    .025       0  4845.8     .07       0
 4986.62     .06       0 5014.48     .07       0  5065.8      .1       0
    5530     .06       0
#Block Obstruct= 2 , 0
       0    4875   220.1               0
Bank Sta=4986.62,5014.48
XS Rating Curve= 0
Exp/Cntr=.5,.3

Type RM Length L Ch R = 1 ,769.1   ,55,52,54.9
BEGIN DESCRIPTION:
K166-01-00-S3_CHARTERLN-XS3
Added in blocked obstruction and mannings n of 0.026 for the pond on the left overbank shown on the sid images. - JJA 3/16/03
END DESCRIPTION:
XS GIS Cut Line= 3
      2941706.79     13937443.19      2940588.51     13937387.61
      2940406.66     13938286.52
#Sta/Elev= 30
    3978  231.52    4238  228.62    4418  222.92    4528  222.52    4578  220.22
    4608  218.92    4818  219.02  4865.8  220.06    4878  220.32  4942.3  217.13
    4987  216.12  4990.9  213.48  4991.7  212.22  4999.7  211.53  5007.6  212.25
  5013.7   216.1  5020.6  217.39  5064.7  219.66  5076.1  219.12  5098.3  216.76
  5117.7  218.42  5157.7  218.42  5187.7  219.32  5227.7  218.12  5297.7  219.42
  5417.7  218.72  5457.7  217.82  5577.7  218.32  5659.4  221.42  6014.8  227.82
#Mann= 8 ,-1 , 0
    3978     .07       0    4578    .026       0  4865.8     .07       0
    4987     .06       0  5013.7     .07       0  5076.1      .1       0
  5659.4     .06       0  6014.8     .99       0
#XS Ineff= 2 , 0
       0 4985.25   217.4 5015.15       0   217.4
Permanent Ineff=
       F       F
#Block Obstruct= 2 , 0
         4866.52   220.1
Bank Sta=4987,5013.7
XS Rating Curve= 0
Exp/Cntr=.5,.3