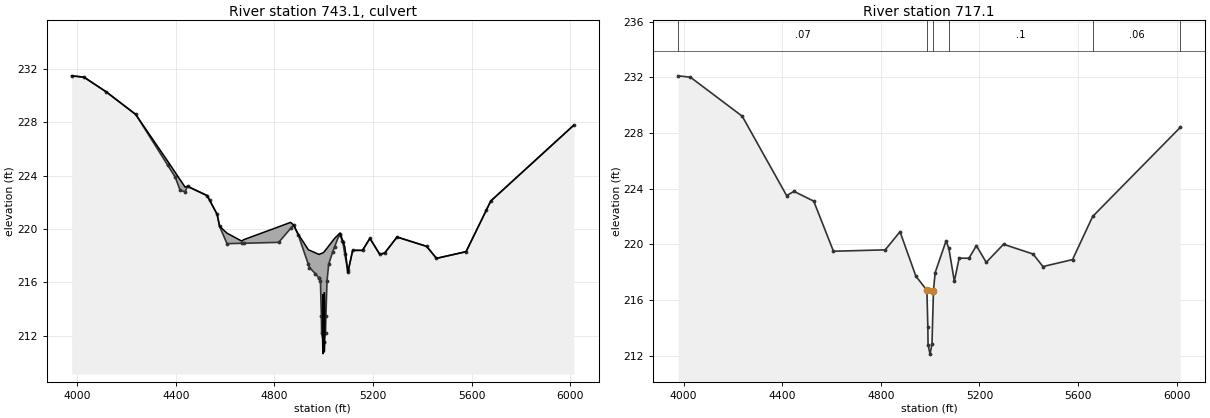
HEC-RAS study K166-01-00.prj: K166-01-00

--- K166-01-00.g01 (geometry) --- (continued)

Type RM Length L Ch R = 2 ,743.1   ,,,
BEGIN DESCRIPTION:
CHARTER LANE
Structure ID: K166-01-00-S3; Lots of weeds in front of culverts 11/14/2 VRR
END DESCRIPTION:
Bridge Culvert--1,0,-1,-1, 0
Deck Dist Width WeirC Skew NumUp NumDn MinLoCord MaxHiCord MaxSubmerge Is_Ogee
10,32,3,0, 55, 55, , , .95, 0, ,,,
    3978    4028    4118    4238  4367.3    4398    4418    4438    4448    4528
  4537.3    4568    4578    4608  4667.3  4675.8    4818  4865.8    4878  4896.8
  4938.1  4942.3  4966.9  4980.4  4981.2    4987  4990.9  4991.7  4999.7  5000.1
  5007.6  5009.2  5013.7  5020.6  5037.4  5044.9  5064.7  5066.5  5076.1  5077.5
    5086  5097.5  5098.3  5117.7  5157.7  5187.7  5227.7  5247.7  5297.7  5417.7
  5457.7  5577.7  5659.4  5677.7  6014.8
   231.5   231.4   230.3   228.6   225.1  224.25   223.7  223.15  223.21  222.51
  222.18  221.11  220.21  219.69   219.1   219.2  220.17   220.5  220.31  219.62
  218.44  218.41  218.21   218.1  218.09  218.14  218.17  218.17  218.24  218.24
  218.42  218.46  218.56  218.73  219.13  219.31  219.67   219.7  219.19  219.11
  218.66  216.89  216.74   218.4   218.4   219.3   218.1   218.2   219.4   218.7
   217.8   218.3   221.4   222.1   227.8
   231.5   231.4   230.3   228.6   224.8   223.9   222.9   222.8   223.2   222.5
  222.17   221.1   220.2   218.9  218.93  218.93     219  220.04   220.3  219.57
  217.34  217.11  216.64  216.34  216.31   216.1  213.46   212.2  211.51  211.55
  212.23  213.49  216.08  217.37  218.31  218.68  219.64  219.55   219.1  219.03
  218.12  216.89  216.74   218.4   218.4   219.3   218.1   218.2   219.4   218.7
   217.8   218.3   221.4   222.1   227.8
    3978    4028    4118    4238  4367.3    4398    4418    4438    4448    4528
  4537.3    4568    4578    4608  4667.3  4675.8    4818  4865.8    4878  4896.8
  4938.1  4942.3  4966.9  4980.4  4981.2    4987  4990.9  4991.7  4999.7  5000.1
  5007.6  5009.2  5013.7  5020.6  5037.4  5044.9  5064.7  5066.5  5076.1  5077.5
    5086  5097.5  5098.3  5117.7  5157.7  5187.7  5227.7  5247.7  5297.7  5417.7
  5457.7  5577.7  5659.4  5677.7  6014.8
  232.05  231.95  230.85  229.15  225.35  224.45   223.7  223.35  223.75  223.05
  222.72  221.65  220.75  219.69  219.48  219.48  220.17  220.59  220.85  220.12
  218.44  218.41  218.21   218.1  218.09  218.14  218.17  218.17  218.24  218.24
  218.42  218.46  218.56  218.73  219.13  219.31  220.19   220.1  219.65  219.58
  218.67  217.44  217.29  218.95  218.95  219.85  218.65  218.75  219.95  219.25
  218.35  218.85  221.95  222.65  228.35
  232.05  231.95  230.85  229.15  225.35  224.45  223.45  223.35  223.75  223.05
  222.72  221.65  220.75  219.45  219.48  219.48  219.55  220.59  220.85  220.12
  217.89  217.66  217.19  216.89  216.86  216.65  214.01  212.75  212.06   212.1
  212.78  214.04  216.63  217.92  218.86  219.23  220.19   220.1  219.65  219.58
  218.67  217.44  217.29  218.95  218.95  219.85  218.65  218.75  219.95  219.25
  218.35  218.85  221.95  222.65  228.35
BR Coef= 1 , 0 , 0 ,1.25, 0 ,,,.8,-1,2,0,
WSPro=,,,, 1 ,,,, 0 ,,,, 0 ,,,,-1 ,-1 ,-1 , 0 , 0 , 0 , 0 , 0
Culvert=1,4.5,,32,.026,.5,1,2,1,210.61,4997.5,211.82,4997.5,Culvert #1  , 0 ,10
Culvert Bottom n=.026
Culvert=1,4.5,,32,.026,.5,1,2,3,210.75,5002.9,212.23,5002.9,Culvert #2  , 0 ,10
Culvert Bottom n=.026
BR U #Sta/Elev= 55
    3978   231.5    4028   231.4    4118   230.3    4238   228.6  4367.3   224.8
    4398   223.9    4418   222.9    4438   222.8    4448   223.2    4528   222.5
  4537.3  222.17    4568   221.1    4578   220.2    4608   218.9  4667.3  218.93
  4675.8  218.93    4818     219  4865.8  220.04    4878   220.3  4896.8  219.57
  4938.1  217.34  4942.3  217.11  4966.9  216.64  4980.4  216.34  4981.2  216.31
    4987   216.1  4990.9  213.46  4991.7   212.2  4999.7  211.51  5000.1  211.55
  5007.6  212.23  5009.2  213.49  5013.7  216.08  5020.6  217.37  5037.4  218.31
  5044.9  218.68  5064.7  219.64  5066.5  219.55  5076.1   219.1  5077.5  219.03
    5086  218.12  5097.5  216.89  5098.3  216.74  5117.7   218.4  5157.7   218.4
  5187.7   219.3  5227.7   218.1  5247.7   218.2  5297.7   219.4  5417.7   218.7
  5457.7   217.8  5577.7   218.3  5659.4   221.4  5677.7   222.1  6014.8   227.8
BR U #Mann= 7
    3978     .07    4578    .026  4865.8     .07    4987     .06  5013.7     .07
  5076.1      .1  5659.4     .06
BR U Banks=4987,5013.7
BR D #Sta/Elev= 55
    3978  232.05    4028  231.95    4118  230.85    4238  229.15  4367.3  225.35
    4398  224.45    4418  223.45    4438  223.35    4448  223.75    4528  223.05
  4537.3  222.72    4568  221.65    4578  220.75    4608  219.45  4667.3  219.48
  4675.8  219.48    4818  219.55  4865.8  220.59    4878  220.85  4896.8  220.12
  4938.1  217.89  4942.3  217.66  4966.9  217.19  4980.4  216.89  4981.2  216.86
    4987  216.65  4990.9  214.01  4991.7  212.75  4999.7  212.06  5000.1   212.1
  5007.6  212.78  5009.2  214.04  5013.7  216.63  5020.6  217.92  5037.4  218.86
  5044.9  219.23  5064.7  220.19  5066.5   220.1  5076.1  219.65  5077.5  219.58
    5086  218.67  5097.5  217.44  5098.3  217.29  5117.7  218.95  5157.7  218.95
  5187.7  219.85  5227.7  218.65  5247.7  218.75  5297.7  219.95  5417.7  219.25
  5457.7  218.35  5577.7  218.85  5659.4  221.95  5677.7  222.65  6014.8  228.35
BR D #Mann= 5
    3978     .07    4987     .06  5013.7     .07  5076.1      .1  5659.4     .06
BR D Banks=4987,5013.7
BC Design=,, 0 ,, 0 ,,,,,,
BC HTab HWMax=231.52

Type RM Length L Ch R = 1 ,717.1   ,0,0,0
BEGIN DESCRIPTION:
K166-01-00-S3_CHARTER LN - XS2
END DESCRIPTION:
XS GIS Cut Line= 3
      2941709.05     13937388.38      2940586.48     13937332.58
      2940403.76     13938235.71
#Sta/Elev= 30
    3978  232.11    4028  232.01    4238  229.21    4418  223.51    4448  223.81
    4528  223.11    4608  219.51    4818  219.61    4878  220.91  4942.3  217.72
    4987  216.71  4990.9  214.07  4991.7  212.81  4999.7  212.12  5007.6  212.84
  5013.7  216.69  5020.6  217.98  5064.7  220.25  5076.1  219.71  5098.3  217.35
  5117.7  219.01  5157.7  219.01  5187.7  219.91  5227.7  218.71  5297.7  220.01
  5417.7  219.31  5457.7  218.41  5577.7  218.91  5659.4  222.01  6014.8  228.41
#Mann= 6 ,-1 , 0
    3978     .07       0    4987     .06       0  5013.7     .07       0
  5076.1      .1       0  5659.4     .06       0  6014.8     .99       0
#XS Ineff= 2 , 0
       0 4985.25  216.74 5015.15       0  216.74
Permanent Ineff=
       F       F
Bank Sta=4987,5013.7
XS Rating Curve= 0
Exp/Cntr=.5,.3

Chan Stop Cuts=-1